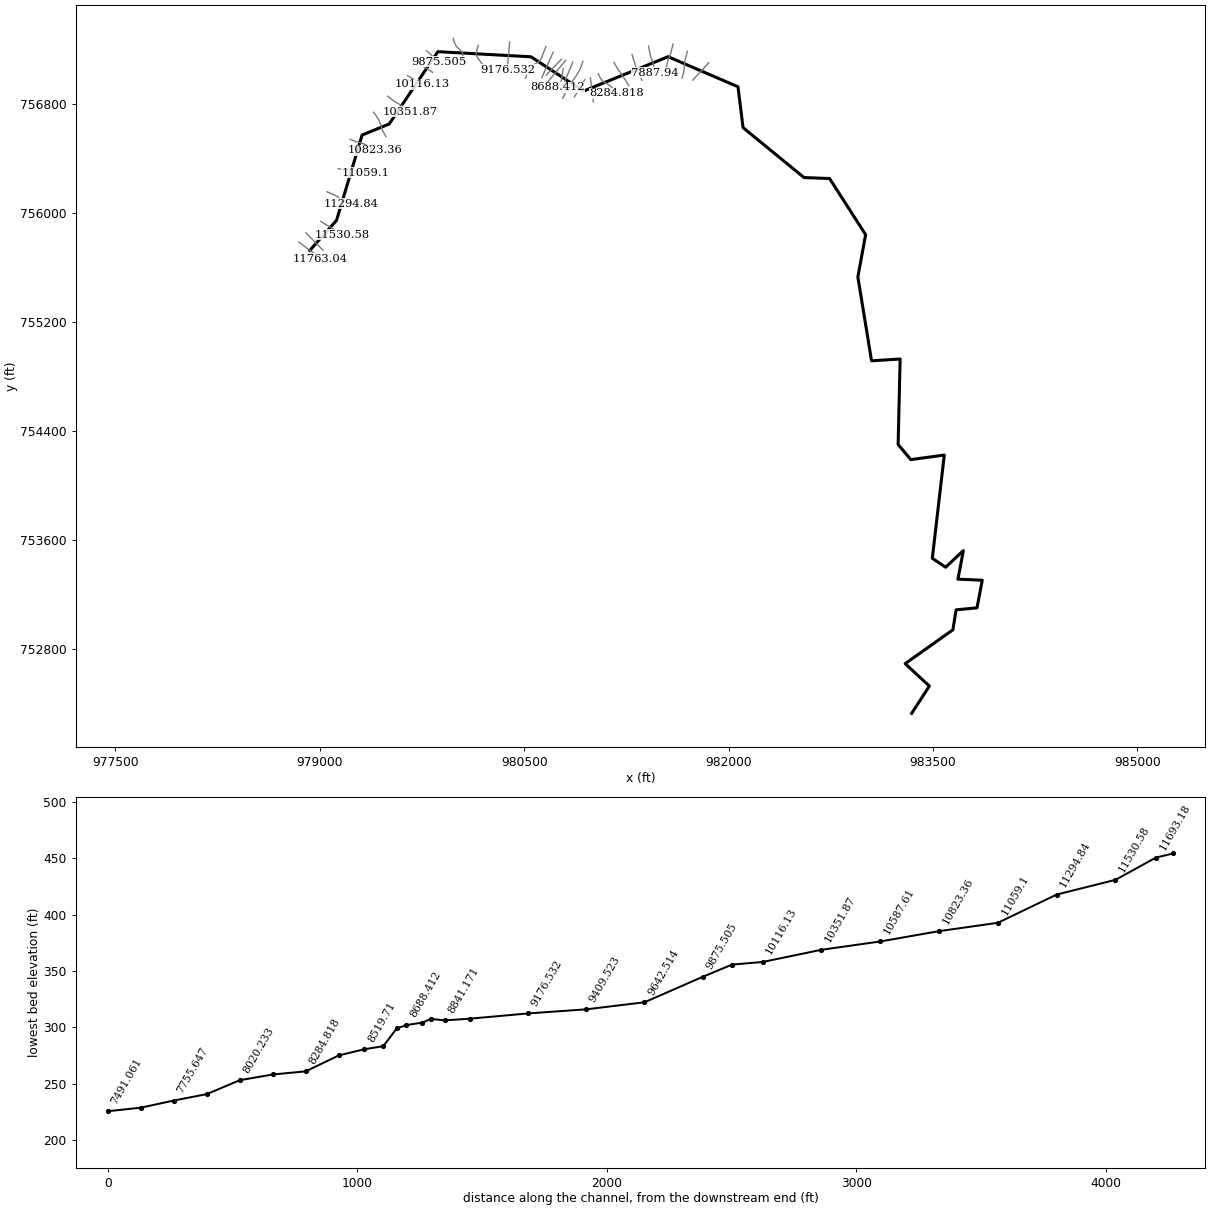
--- 43_ras.prj (project) ---

Proj Title=43
Current Plan=p01
Default Exp/Contr=0.3,0.1
English Units
Geom File=g01
Flow File=f01
Plan File=p01
Y Axis Title=Elevation
X Axis Title(PF)=Main Channel Distance
X Axis Title(XS)=Station
BEGIN DESCRIPTION:
RFD model 43 exported to HEC-RAS
END DESCRIPTION:

--- 43_ras.p01 (plan) ---

Plan Title=Plan 01
Program Version=4.10
Short Identifier=Plan 01
Geom File=g01
Flow File=f01
Subcritical Flow
Calc Critical at every XS
Secant Critical Depth

--- 43_ras.f01 (steady flow) ---

Flow Title=Flow 01
Program Version=5.01
Number of Profiles= 6
Profile Names=10yr,25yr,50yr,100yr,100plus,500yr
River Rch & RM=43,75,11763.04
   80.73  151.64  227.17   309.5  451.87 1029.82
River Rch & RM=43,75,9176.532
    93.9  176.45  264.43   360.3  526.03 1173.37
River Rch & RM=43,75,8943.541
   96.51  181.38  271.84  370.41  540.81 1201.72
River Rch & RM=43,75, 8787.53
   98.03  184.24  276.15  376.29  549.39 1218.13
River Rch & RM=43,75,8688.412
  102.55  192.76  288.98  393.81  574.96 1266.86
River Rch & RM=43,75,8595.541
  104.47  196.39  294.44  401.27  585.86 1287.52
River Rch & RM=43,75,8417.111
  105.11   197.6  296.26  403.75  589.48 1294.38
River Rch & RM=43,75,8284.818
  144.18  272.02   408.9  558.33  815.16 1716.49
River Rch & RM=43,75,8152.525
  146.95  277.28  416.82  569.14  830.95 1745.01
River Rch & RM=43,75,8020.233
  148.14  279.52   420.2  573.77   837.7 1757.17
River Rch & RM=43,75, 7887.94
  149.52  282.13  424.14  579.15  845.56 1771.33
River Rch & RM=43,75,7755.647
  159.24  300.56  451.95   617.2  901.11 1871.17
River Rch & RM=43,75,7623.354
  161.14  304.17  457.42   624.7  912.06 1890.89
River Rch & RM=43,75,7491.061
  162.28  306.34   460.7  629.19  918.62 1902.68
River Rch & RM=43,75,7392.538
   163.8  309.23  465.07  635.19  927.37 1918.36
River Rch & RM=43,75,7294.014
  169.64  320.35  481.89  658.26  961.06 1978.64
River Rch & RM=43,75,7195.491
  171.32  323.56  486.75  664.93   970.8 1996.01
River Rch & RM=43,75,7047.706
  173.56  327.82  493.22   673.8  983.75 2019.07
River Rch & RM=43,75,6850.659
  176.36  333.14  501.27  684.85  999.88 2047.75
River Rch & RM=43,75,6568.418
  177.47  335.27  504.49  689.26 1006.32 2059.18
River Rch & RM=43,75, 6335.44
  183.35  346.49   521.5  712.63 1040.44 2119.72
River Rch & RM=43,75,6102.461
  185.16  349.95  526.76  719.86    1051 2138.51
River Rch & RM=43,75,5869.482
  193.26  365.46  550.32  752.27 1098.32 2222.23
River Rch & RM=43,75,5636.503
  196.37  371.47   559.5  764.98 1116.86 2255.38
River Rch & RM=43,75,5537.286
  197.74  374.13  563.57   770.6 1125.08 2270.05
River Rch & RM=43,75,5420.401
  198.93  376.44   567.1   775.5 1132.23 2282.85
River Rch & RM=43,75, 5175.78
  236.52  448.66   677.1  927.17 1353.67  2668.8
River Rch & RM=43,75, 4931.16
  249.85  474.53  716.75  982.14 1433.93  2808.3
River Rch & RM=43,75,4686.539
   256.7  487.78  737.02 1010.19 1474.88 2878.71
River Rch & RM=43,75,4441.919
  259.87  493.96  746.51 1023.37 1494.12    2912
River Rch & RM=43,75,4197.298
  260.83  495.82  749.36 1027.33 1499.91 2921.95
River Rch & RM=43,75,3952.678
   263.8  501.62  758.29 1039.76 1518.04  2953.4
River Rch & RM=43,75,3708.057
  268.25  510.35  771.76 1058.55 1545.48 3001.14
River Rch & RM=43,75,3463.436
  269.92  513.64  776.84 1065.64 1555.83 3019.17
River Rch & RM=43,75,3218.816
  270.53  514.83  778.68 1068.21 1559.59 3025.72
River Rch & RM=43,75,2974.195
  274.78  523.18  791.58 1086.22 1585.88 3071.39
River Rch & RM=43,75,2729.575
  277.66  528.83   800.3  1098.4 1603.66 3102.23
River Rch & RM=43,75,2484.954
  280.83  535.06  809.94 1111.84 1623.29 3136.17
River Rch & RM=43,75,2203.085
  284.27  541.83  820.41 1126.48 1644.66 3173.19
River Rch & RM=43,75,1945.582
  284.87  543.01  822.23 1129.02 1648.38 3179.61
River Rch & RM=43,75,1491.192
   285.6  544.46  824.48 1132.18 1652.98 3187.63
River Rch & RM=43,75,1248.556
  311.76  595.94  904.11 1243.46 1815.45  3466.6
River Rch & RM=43,75, 1005.92
  313.75  599.88  910.24 1252.07 1828.02 3488.28
River Rch & RM=43,75,763.2839
  316.74  605.82  919.46    1265 1846.89 3520.71
River Rch & RM=43,75,520.6478
  320.13  612.55  929.92  1279.7 1868.35 3557.63
River Rch & RM=43,75,278.0116
  321.54  615.35  934.28 1285.81 1877.28 3572.97
River Rch & RM=43,75, 35.3755
  322.24  616.74  936.45 1288.86 1881.74 3580.63
Boundary for River Rch & Prof#=43,75,1
Up Type= 0
Dn Type= 2
Boundary for River Rch & Prof#=43,75,2
Up Type= 0
Dn Type= 2
Boundary for River Rch & Prof#=43,75,2
Up Type= 0
Dn Type= 2
Boundary for River Rch & Prof#=43,75,2
Up Type= 0
Dn Type= 2
Boundary for River Rch & Prof#=43,75,2
Up Type= 0
Dn Type= 2
Boundary for River Rch & Prof#=43,75,2
Up Type= 0
Dn Type= 2

--- 43_ras.g01 (geometry) ---

Geom Title=43
Program Version=4.10

River Reach=43,75
Reach XY= 30
978927.566301513755726.192228047979123.467850479755946.683929564
 979311.17268184756572.913148714979510.352917791756654.060652223
979866.910130234757184.388276278980550.516372133757146.683375683
980934.942424193 756895.04414755981556.253612849757147.503047429
982069.006674114756926.746388001982106.253358977756627.011484405
 982553.48707788756260.804196085  982740.8796732756253.710634437
983005.433271797755841.765945185982948.486297565755531.562589679
  983048.8758747754916.356536276983258.711843405754929.471284312
983243.936297492754301.869139912983337.254105199754191.359100025
983582.482185753754224.553576892983494.777308213753467.176877302
983592.318246812753401.603137105983722.646055462753523.734228242
983682.733745235753314.103557997983861.170581714753306.521213766
983822.601040038753103.619392223983669.367391558753089.308199262
983645.749429079752942.433708851983295.597072303752694.226414381
 983473.08744705752529.867906839983343.138033941752329.472484386

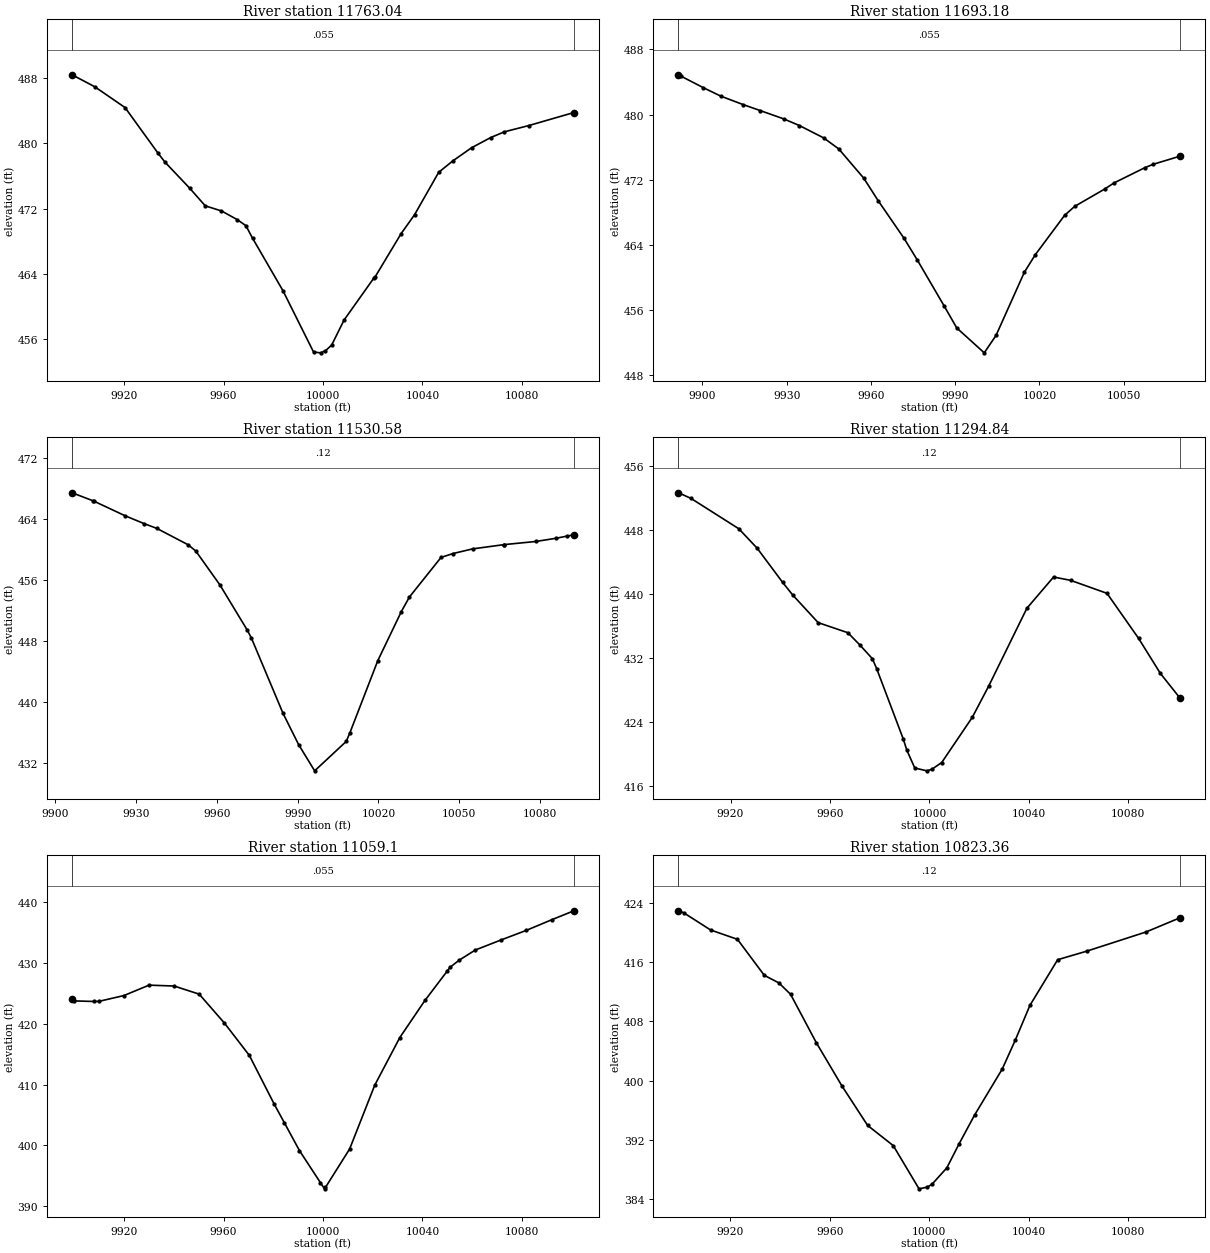
Type RM Length L Ch R = 1 ,11763.04,69.860000,69.860000,69.860000
XS GIS Cut Line= 6
978847.821938709755788.220636671978900.011297114755747.000689293
 978927.29351457755727.579883366978928.953956832 755726.46501499
978953.559195724755708.542572857979006.161872881755663.062388056
#Sta/Elev= 28
9899.007488.41319908.154486.94389920.337484.3949 9933.64478.79399936.471477.6886
9946.383474.50939952.605472.36129959.126471.73889965.511 470.6689968.961469.9321
9971.635468.4018 9983.91461.95249996.185454.4587    9999454.3575   10001454.6184
10003.49455.310610008.48458.376610020.47463.521110020.85463.597510031.44468.9617
10036.86471.280110046.56476.468410052.15477.842110059.78479.473610067.44 480.717
   10073481.427810082.73482.186110100.98483.7919
#Mann= 3 , 0 , 0
9899.007   0.055       09899.007   0.055       010100.98   0.055       0
#XS Ineff= 2 , 0
       0                               0
Bank Sta=9899.007,10100.98
Exp/Cntr=0.3,0.1

Type RM Length L Ch R = 1 ,11693.18,162.592400,162.592400,162.592400
XS GIS Cut Line= 2
978898.840107501 755855.74836646979023.840107501755728.144199774
#Sta/Elev= 27
9891.506484.88989892.554484.69259900.309483.31059906.552482.26529914.599481.2127
9920.551480.49569928.889479.4748 9934.55 478.6489943.179477.12729948.548475.7751
 9957.47472.16619962.547 469.424 9971.76464.79379976.545462.0932 9986.05456.4701
9990.544453.758710000.34450.693910004.54452.838610014.63460.616710018.54462.7735
10028.92467.595310032.54468.708210043.21470.837510046.54471.5903 10057.5473.4636
10060.54473.889210070.13474.8929
#Mann= 3 , 0 , 0
9891.506   0.055       09891.506   0.055       010070.13   0.055       0
#XS Ineff= 2 , 0
       0                               0
Bank Sta=9891.506,10070.13
Exp/Cntr=0.3,0.1

Type RM Length L Ch R = 1 ,11530.58,235.742900,235.742900,235.742900
XS GIS Cut Line= 2
979008.215107501755939.081699789979167.069274187755841.425449789
#Sta/Elev= 28
 9906.17467.47989913.964466.42439914.135466.40349925.873464.45839933.059463.4065
9937.612462.8073 9949.35460.63359952.154459.81639961.089455.37329971.248449.4367
9972.827448.36459984.566438.47149990.343434.37669996.304430.924410008.04434.7929
10009.44435.959610019.78445.421710028.53451.871410031.52453.778110043.26  458.98
10047.63 459.483   10055460.104210066.72 460.66610066.74460.666510078.47461.0771
10085.82461.489210090.21461.791810092.64461.9589
#Mann= 3 , 0 , 0
 9906.17    0.12       0 9906.17    0.12       010092.64    0.12       0
#XS Ineff= 2 , 0
       0                               0
Bank Sta=9906.17,10092.64
Exp/Cntr=0.3,0.1

Type RM Length L Ch R = 1 ,11294.84,235.742900,235.742900,235.742900
XS GIS Cut Line= 6
979052.487354318756156.872618296979119.288328557756127.796274383
979134.009347446756118.187692765979148.540615103756104.066073777
979160.682577475756097.022900859979232.463690558756068.865869499
#Sta/Elev= 26
9899.051 452.6799904.046 451.9829923.335448.17319930.717 445.7359940.964 441.456
9945.018439.8747 9955.24436.42119967.186435.1581 9971.94433.65189977.056 431.904
 9978.76430.67759989.519421.82299990.896420.46979994.109418.2183    9999417.8647
   10001418.063310004.96418.908110017.26424.570310023.83428.462810039.21438.2209
10049.95442.130810056.76441.720710071.44 440.09110084.14434.454910092.92430.0618
10100.94426.9219
#Mann= 3 , 0 , 0
9899.051    0.12       09899.051    0.12       010100.94    0.12       0
#XS Ineff= 2 , 0
       0                               0
Bank Sta=9899.051,10100.94
Exp/Cntr=0.3,0.1

Type RM Length L Ch R = 1 , 11059.1,235.742900,235.742900,235.742900
XS GIS Cut Line= 5
 979134.29053499756326.139075704 979233.39675766756313.104426085
979235.375679788756312.814827724979283.932190371756305.970981422
979333.786934165756295.548582999
#Sta/Elev= 28
 9899.04424.05259899.756423.77279907.776423.67579909.842423.69569919.928 424.653
9930.014426.3657  9940.1426.21949950.186424.88169960.273420.15349970.359414.7982
9980.445406.71279984.463403.70189990.531399.1198    9999393.817110000.62392.8171
   10001393.052510010.72399.378710020.82409.880410030.92417.736910041.02423.8434
10050.04428.708110051.13429.307310054.78430.469510061.34432.158210071.56433.7916
10081.78435.379410091.99 437.12710100.97438.6129
#Mann= 3 , 0 , 0
 9899.04   0.055       0 9899.04   0.055       010100.97   0.055       0
#XS Ineff= 2 , 0
       0                               0
Bank Sta=9899.04,10100.97
Exp/Cntr=0.3,0.1

Type RM Length L Ch R = 1 ,10823.36,235.742800,235.742800,235.742800
XS GIS Cut Line= 6
979223.027521902756541.486740973979260.482847159756526.261756583
979314.446120731756512.418259189979319.568670229756509.832163882
979367.349516042756486.335887745979406.587290789756460.984062659
#Sta/Elev= 24
9899.118422.89959901.247 422.6249912.042420.31049922.837419.05279933.631414.2024
 9939.55413.16949944.213411.63829954.537405.13089964.861399.29339975.185393.9745
9985.508391.24959995.876385.4267    9999385.6433   10001386.011910007.05388.2544
10011.95391.4723 10018.2395.364410029.34401.572710034.61405.487210040.48410.1577
10051.63416.305710063.35417.460910087.17420.043210100.96421.9728
#Mann= 3 , 0 , 0
9899.118    0.12       09899.118    0.12       010100.96    0.12       0
#XS Ineff= 2 , 0
       0                               0
Bank Sta=9899.118,10100.96
Exp/Cntr=0.3,0.1

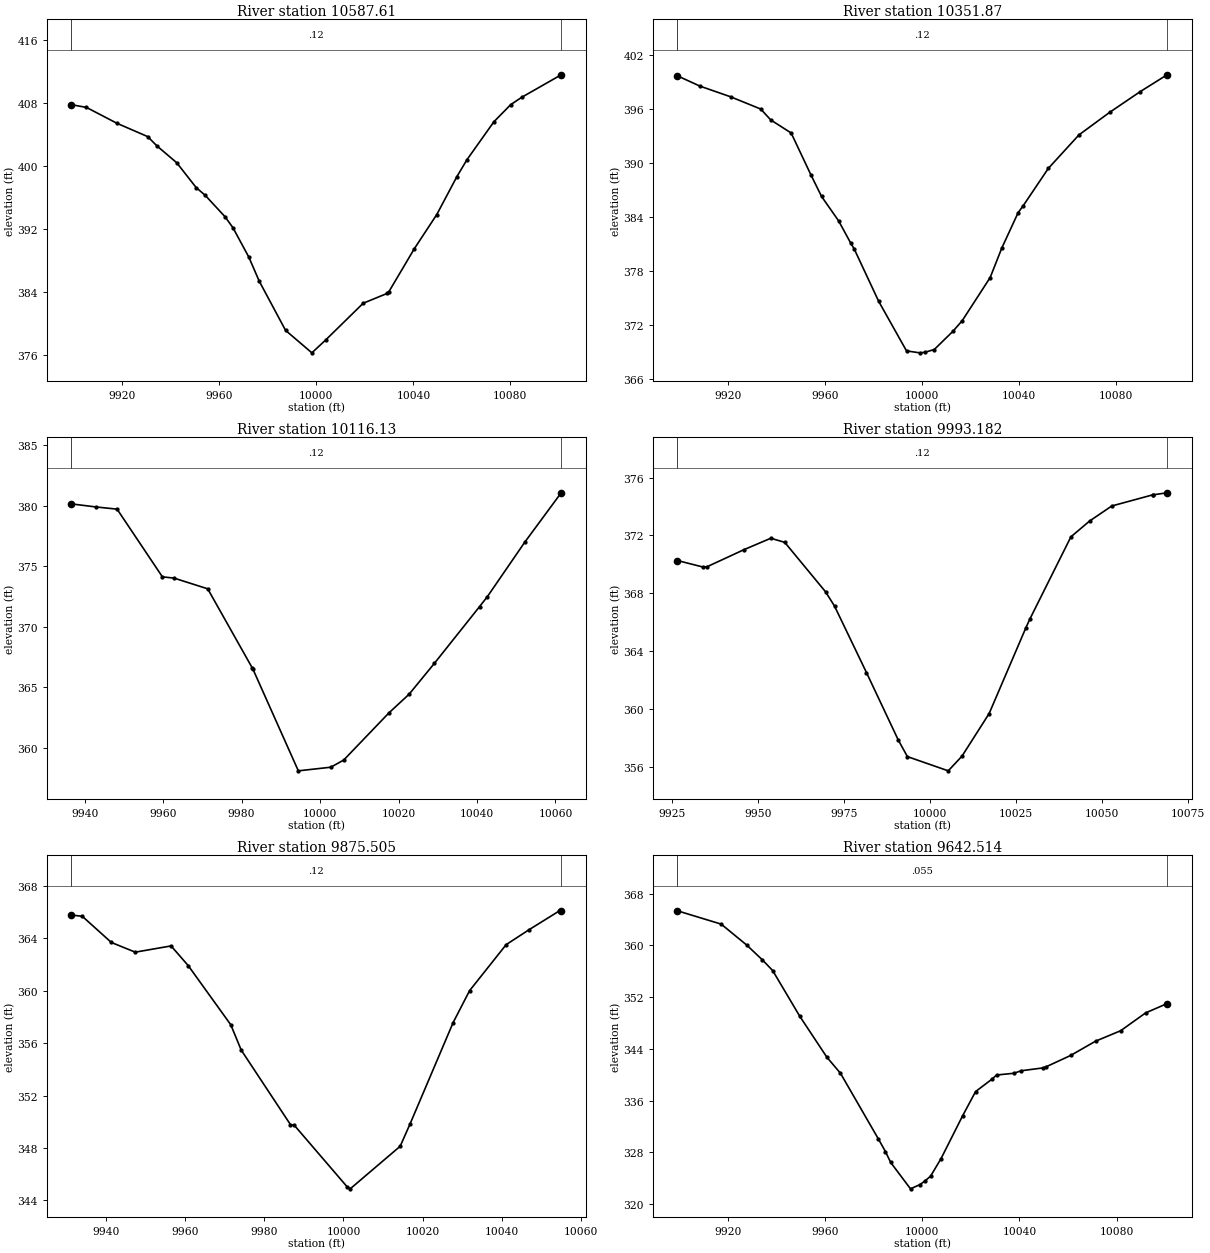
Type RM Length L Ch R = 1 ,10587.61,235.742900,235.742900,235.742900
XS GIS Cut Line= 6
979395.070902499756739.888307045 979416.60106733 756711.90469469
 979431.20747733756688.039119042979447.116471293756649.744635942
979461.382170764 756606.19206841 979485.78707663756561.123297489
#Sta/Elev= 26
9899.053 407.7479905.221407.40569917.838405.38459930.455403.70359934.361402.4999
9942.456400.3817 9950.45397.2351 9954.18396.25099962.341393.53849965.636392.1295
 9972.16388.41289976.477385.34489987.319379.1101 9998.16376.258510003.81377.8776
10019.33382.554910029.14383.789710029.85383.982810040.37389.458810049.64393.8017
10057.93398.611310062.08400.762110073.19405.578710080.14407.758110084.72408.6962
10100.95411.5457
#Mann= 3 , 0 , 0
9899.053    0.12       09899.053    0.12       010100.95    0.12       0
#XS Ineff= 2 , 0
       0                               0
Bank Sta=9899.053,10100.95
Exp/Cntr=0.3,0.1

Type RM Length L Ch R = 1 ,10351.87,235.742900,235.742900,235.742900
XS GIS Cut Line= 6
 979497.58939357756858.216033043979550.621417026756818.110631491
979579.778015961756801.704290556979581.566870343756800.809863366
979616.689466336756780.668973533979663.754371192756744.340504634
#Sta/Elev= 27
9899.055399.70089908.346398.55559920.965397.37099933.421396.00569937.544394.7942
9945.959393.34439954.123  388.689958.497386.28599965.544383.56799970.569381.0741
9971.888 380.4879982.043374.62779993.517369.1145    9999 368.897   10001368.9494
10004.96369.265410012.68371.298910016.49372.475410028.01377.271910032.78380.5361
10039.54384.486710041.49385.201910051.99389.408610064.62393.132910077.25 395.634
10089.88397.945110100.94399.8142
#Mann= 3 , 0 , 0
9899.055    0.12       09899.055    0.12       010100.94    0.12       0
#XS Ineff= 2 , 0
       0                               0
Bank Sta=9899.055,10100.94
Exp/Cntr=0.3,0.1

Type RM Length L Ch R = 1 ,10116.13,122.945100,122.945100,122.945100
XS GIS Cut Line= 2
 979644.93385753757008.092116445979753.006774187756945.592116445
#Sta/Elev= 19
9936.622380.15479936.698 380.1519942.798379.9041 9948.25379.72069959.802374.1223
9962.773374.01739971.354 373.1329982.748 366.5689982.906366.47239994.457358.0789
10002.72358.378610006.01358.966110017.56362.8737 10022.7364.417210029.11366.9565
10040.66371.661810042.67372.495310052.22377.005910061.47381.0742
#Mann= 3 , 0 , 0
9936.622    0.12       09936.622    0.12       010061.47    0.12       0
#XS Ineff= 2 , 0
       0                               0
Bank Sta=9936.622,10061.47
Exp/Cntr=0.3,0.1

Type RM Length L Ch R = 1 ,9993.182,117.677600,117.677600,117.677600
XS GIS Cut Line= 2
979708.735940844757109.654616445979828.527607501757032.831699789
#Sta/Elev= 22
9926.554370.27189933.996369.82059935.176369.83999945.875371.01629953.701371.8082
9957.755371.52719969.635368.10349972.225367.12159981.514362.52599990.749357.8691
9993.394 356.72410005.27355.739910009.27356.758210017.15359.6977 10027.8365.6081
10029.03366.249410040.91371.905910046.32372.994910052.79374.038710064.67374.8063
10064.85374.809910068.86374.9505
#Mann= 3 , 0 , 0
9926.554    0.12       09926.554    0.12       010068.86    0.12       0
#XS Ineff= 2 , 0
       0                               0
Bank Sta=9926.554,10068.86
Exp/Cntr=0.3,0.1

Type RM Length L Ch R = 1 ,9875.505,232.990800,232.990800,232.990800
XS GIS Cut Line= 2
979782.954690814 757191.68586646979875.402607501757109.654616445
#Sta/Elev= 20
9931.369 365.7859934.104365.68579941.443363.68839947.473362.9487 9956.51363.4255
9960.842361.91889971.576 357.4049974.211355.46969986.643349.7783 9987.58349.7397
10000.95 345.02810001.71344.877710014.32348.128210016.78 349.80810027.69357.5745
10031.84360.010510041.06363.521510046.91364.675510054.43366.088410054.96366.1089
#Mann= 3 , 0 , 0
9931.369    0.12       09931.369    0.12       010054.96    0.12       0
#XS Ineff= 2 , 0
       09962.345                       0
Bank Sta=9931.369,10054.96
Exp/Cntr=0.3,0.1

Type RM Length L Ch R = 1 ,9642.514,232.990800,232.990800,232.990800
XS GIS Cut Line= 6
979979.485306293757282.236575481979989.897568245757248.815066982
980002.175687933757223.955042686980048.709469081757176.983592544
 980049.90863841757155.888243092980037.788064999757106.418998516
#Sta/Elev= 29
9899.143365.35499917.197363.28919927.671360.06089934.149357.76299938.404356.1014
9949.557349.0306 9960.71342.70169966.286340.2316  9981.9330.07139984.848328.0892
9986.977326.4295 9995.15322.3368    9999322.9899   10001 323.51810003.43324.3033
10007.71327.0041 10016.6333.628810021.95337.384810028.57339.2689 10030.6339.9451
 10037.7340.215510040.75 340.60510049.88341.055110050.79341.183710061.09342.9716
10071.38345.186210081.68346.796810091.97349.556210100.81350.9966
#Mann= 3 , 0 , 0
9899.143   0.055       09899.143   0.055       010100.81   0.055       0
#XS Ineff= 2 , 0
       0                               0
Bank Sta=9899.143,10100.81
Exp/Cntr=0.3,0.1

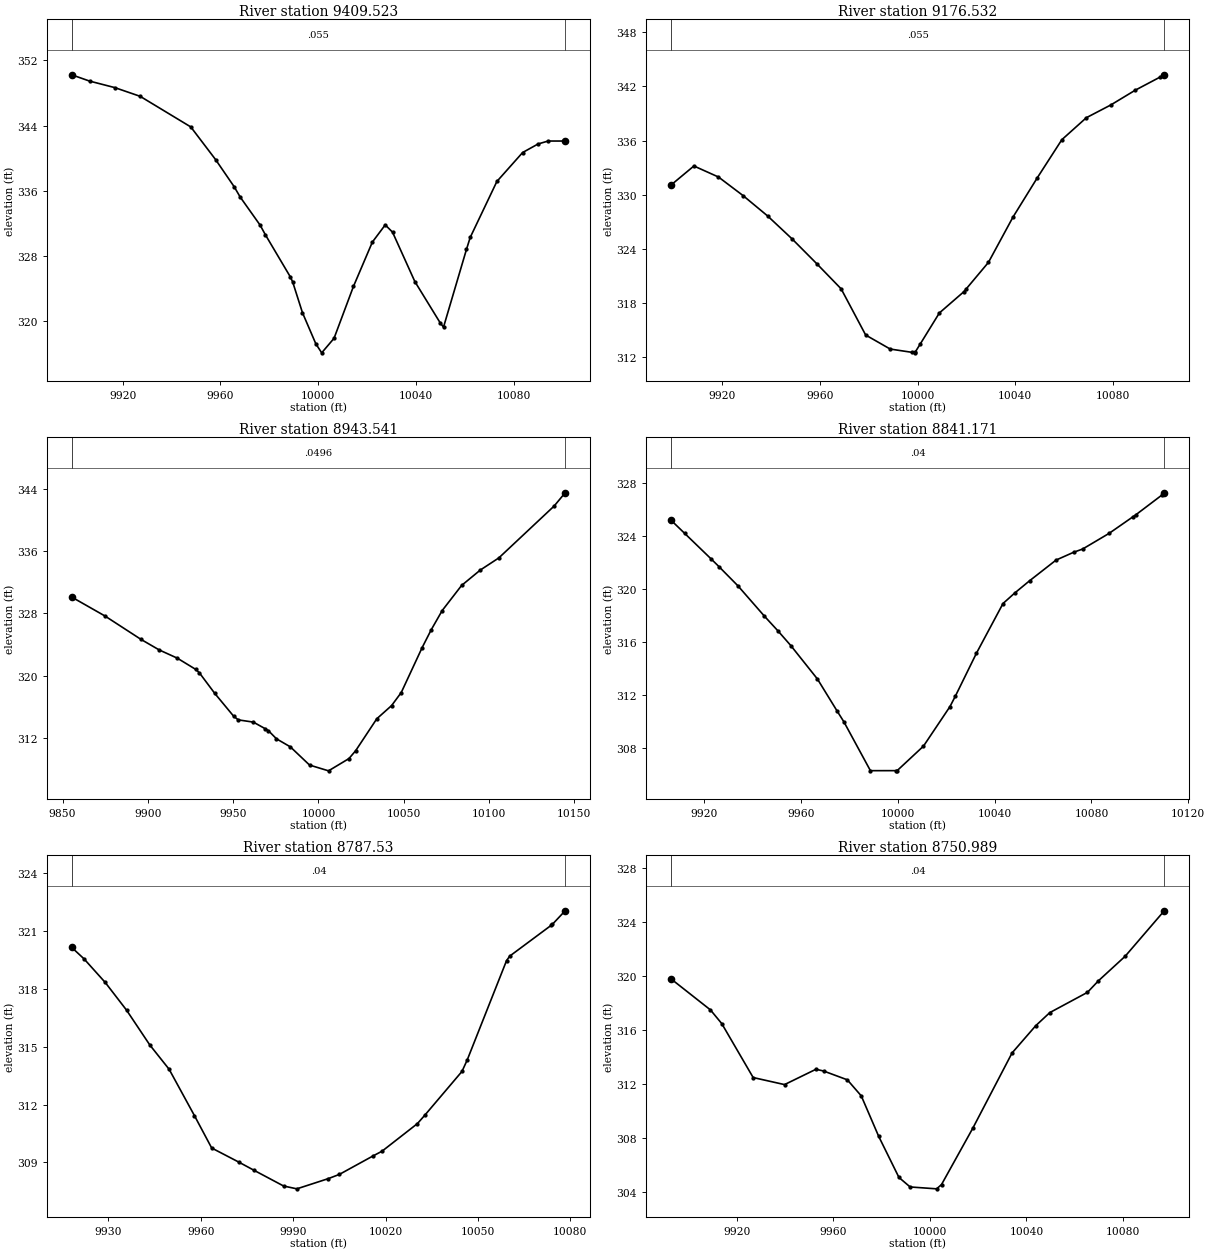
Type RM Length L Ch R = 1 ,9409.523,232.990800,232.990800,232.990800
XS GIS Cut Line= 6
980163.092643681757232.073893284980149.968787455 757182.67085398
980149.494317704757156.902348009980157.207802731757141.402371973
980190.700231622 757096.23837658980208.139012331 757048.32160428
#Sta/Elev= 30
9899.148350.24459906.467349.47089916.814348.66719927.161347.59929947.854343.8433
9957.986339.83929965.623336.48969968.053335.23789976.211331.78469978.335330.6178
9988.568325.43099989.505324.82699993.524321.0377    9999317.211110001.39316.1071
10006.44317.892210014.38324.265410022.11329.705510027.37331.814910030.35330.9261
10039.47324.864610049.85319.7855 10051.2319.261210060.59328.807910062.11330.2695
10073.02337.144710083.55340.699210089.86341.748710093.97342.110910100.94342.1099
#Mann= 3 , 0 , 0
9899.148   0.055       09899.148   0.055       010100.94   0.055       0
#XS Ineff= 2 , 0
       0                10026.79       0
Bank Sta=9899.148,10100.94
Exp/Cntr=0.3,0.1

Type RM Length L Ch R = 1 ,9176.532,232.990800,232.990800,232.990800
XS GIS Cut Line= 5
980394.087629378757254.436698147980384.871154715757154.877419435
980384.574473808 757152.89954673980382.422264655757134.121009042
980377.872454734757053.156166582
#Sta/Elev= 26
9899.015331.04569908.492333.18079918.535331.95959928.578329.9046 9938.62327.6488
9948.663325.09899958.706322.36369968.749319.55879978.791314.43699988.834312.8832
9997.602312.52479998.877312.4635    9999312.5178   10001313.390110008.95316.8861
10019.02319.2517 10019.9319.541310029.04322.495110039.05327.502110049.07331.8898
10059.08336.0978 10069.1338.532310079.12339.948410089.13341.585910099.15343.0197
10100.99343.2937
#Mann= 3 , 0 , 0
9899.015   0.055       09899.015   0.055       010100.99   0.055       0
#XS Ineff= 2 , 0
       0                               0
Bank Sta=9899.015,10100.99
Exp/Cntr=0.3,0.1

Type RM Length L Ch R = 1 ,8943.541,102.370400,102.370400,102.370400
XS GIS Cut Line= 6
  980660.7931922757223.334449953980622.565028054757127.571771125
980608.043611349    757111.82226980553.086078575757077.527495496
980530.910375047757041.708760206980509.308117523756989.016108008
#Sta/Elev= 30
9855.361 330.0979874.813327.67759896.032 324.6689906.642323.32529917.251322.2705
9928.113320.82359930.213320.39269939.236317.75429950.358314.81759953.057314.3592
9961.835314.0751 9968.62 313.2529970.733312.96459975.416311.93429983.557310.9011
9994.791308.572110005.92307.831510017.86 309.39810021.76310.390710034.21314.5032
10042.89 316.19410048.55317.8661 10060.8323.623610066.12325.908710072.55328.3682
10083.92331.583610094.91333.560110105.72 335.10610138.14341.752110144.61 343.454
#Mann= 3 , 0 , 0
9855.361  0.0496       09855.361  0.0496       010144.61  0.0496       0
#XS Ineff= 2 , 0
       0                               0
Bank Sta=9855.361,10144.61
Exp/Cntr=0.3,0.1

Type RM Length L Ch R = 1 ,8841.171,53.640600,53.640600,53.640600
XS GIS Cut Line= 2
980713.127342075757180.283247247980629.712628514756994.204270899
#Sta/Elev= 29
9906.148325.17859911.938324.15989922.897322.22899926.017321.66979933.856320.2224
9944.814317.93399950.463316.81299955.773315.70539966.732313.1943 9974.91 310.768
9977.691  309.969988.649306.27869999.356306.28069999.608306.265810010.57308.1274
10021.53 311.111 10023.8311.914510032.48315.139710043.44318.878910048.25319.6655
 10054.4320.591510065.36322.1538 10072.7322.748410076.32322.984610087.28324.1669
10097.14325.418410098.24325.5558 10109.2327.069710110.07327.2274
#Mann= 3 , 0 , 0
9906.148    0.04       09906.148    0.04       010110.07    0.04       0
#XS Ineff= 2 , 0
       0                               0
Bank Sta=9906.148,10110.07
Exp/Cntr=0.3,0.1

Type RM Length L Ch R = 1 , 8787.53,36.541400,36.541400,36.541400
XS GIS Cut Line= 2
980772.538024187757127.883783117980661.860940814 757011.99836646
#Sta/Elev= 25
9918.062320.1428 9922.05319.55269928.976318.32289935.878316.89219943.455315.0818
9949.706313.82829957.934311.42439963.534309.74629972.413309.00969977.362308.5846
9986.891307.7768 9991.19307.630710001.37308.158310005.02308.380510015.85309.3289
10018.85 309.58110030.33311.009710032.67311.433210044.81313.7156 10046.5314.3049
10059.28 319.45610060.33319.692210073.76321.283610074.16321.335510078.31322.0389
#Mann= 3 , 0 , 0
9918.062    0.04       09918.062    0.04       010078.31    0.04       0
#XS Ineff= 2 , 0
       0                               0
Bank Sta=9918.062,10078.31
Exp/Cntr=0.3,0.1

Type RM Length L Ch R = 1 ,8750.989,62.577100,62.577100,62.577100
XS GIS Cut Line= 2
980805.525178611757121.251296133980674.628243506756964.046643704
#Sta/Elev= 22
9892.545319.79759908.994317.48739913.692316.47199926.705312.48279939.718 311.961
 9952.73313.09479955.878312.96719965.743312.31379971.506311.12849978.756308.1234
9987.134305.09179991.769 304.38710002.76304.248410004.78304.565510017.79308.7483
10034.02314.301310043.82316.315410049.65317.284910065.27318.785410069.85319.6452
 10080.9321.455310097.11324.8213
#Mann= 3 , 0 , 0
9892.545    0.04       09892.545    0.04       010097.11    0.04       0
#XS Ineff= 2 , 0
       0                               0
Bank Sta=9892.545,10097.11
Exp/Cntr=0.3,0.1

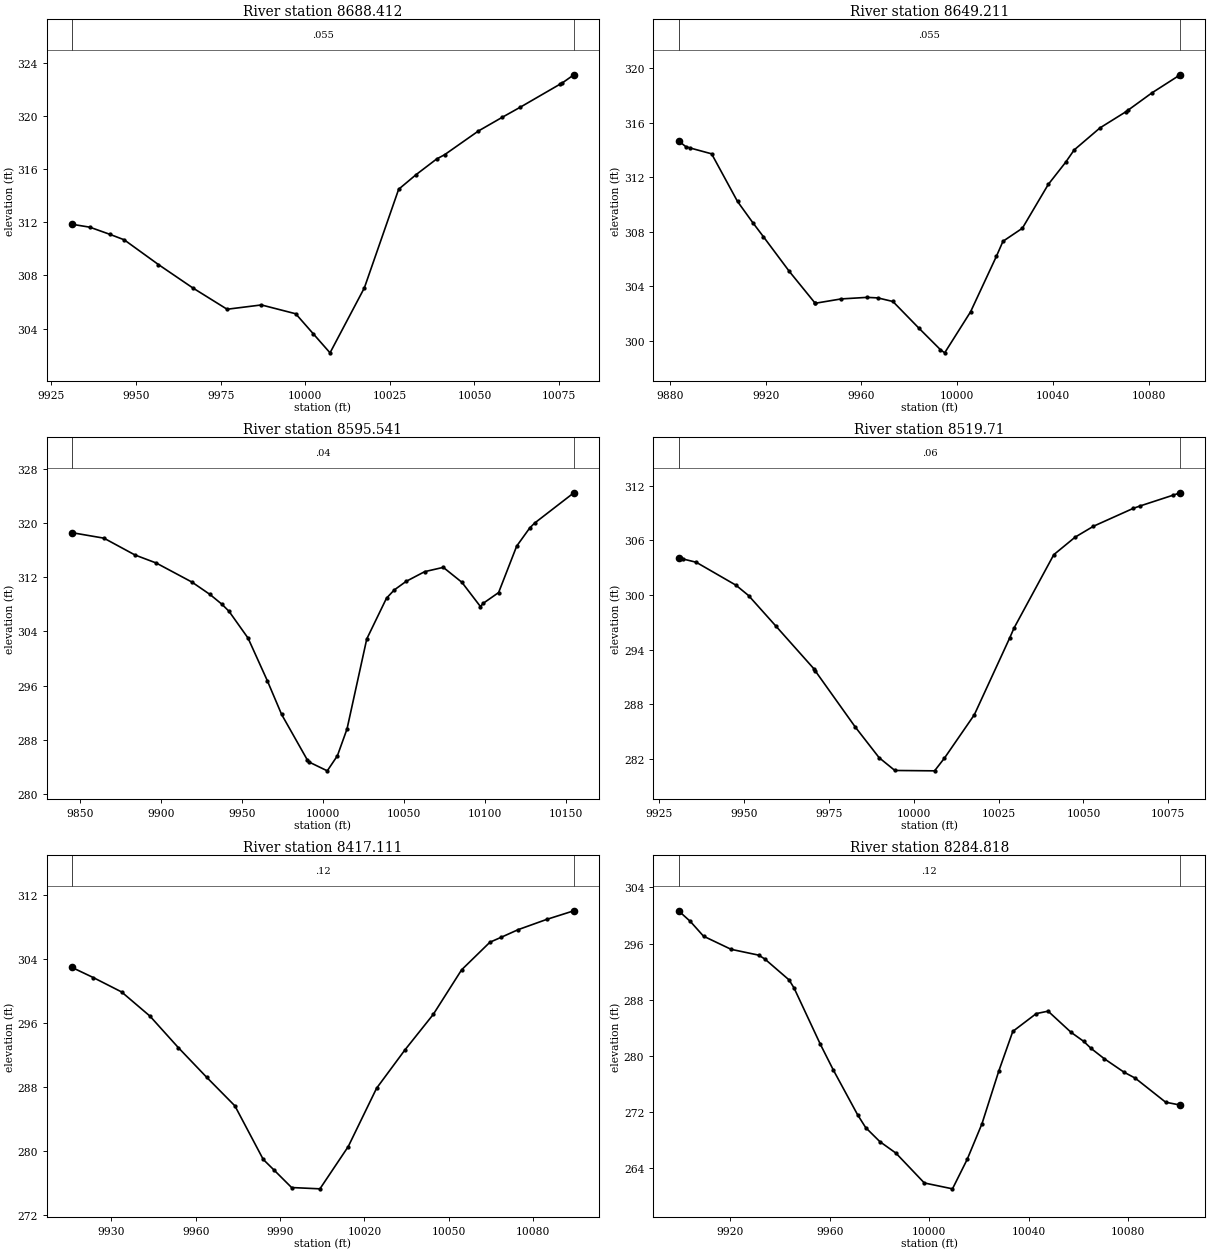
Type RM Length L Ch R = 1 ,8688.412,39.201200,39.201200,39.201200
XS GIS Cut Line= 3
980786.860940814757060.175449774980769.933857501756959.915033132
980742.590107501756922.154616445
#Sta/Elev= 22
9931.081311.8582 9936.33311.63949942.259   311.19946.471310.69059956.613308.8212
9966.754 307.0629976.896305.45299987.037305.77769997.179305.111610002.33 303.613
10007.32302.166310017.46307.0625 10027.6314.499310032.76315.602310038.83 316.782
10041.17317.101810051.18318.893110058.22319.925510063.52320.682210075.27322.4176
10075.87322.498610079.38323.1302
#Mann= 3 , 0 , 0
9931.081   0.055       09931.081   0.055       010079.38   0.055       0
#XS Ineff= 2 , 0
       0                               0
Bank Sta=9931.081,10079.38
Exp/Cntr=0.3,0.1

Type RM Length L Ch R = 1 ,8649.211,53.669300,53.669300,53.669300
XS GIS Cut Line= 2
980856.857310027757107.776611656980776.650854737756913.997815564
#Sta/Elev= 30
9883.581314.66459886.586314.24259888.437314.14079897.408313.71279908.231310.2203
9914.585308.67469919.054307.63759929.877305.09389940.699302.75719940.733302.7577
9951.522 303.0759962.345303.1889 9966.88303.15049973.168302.8868 9983.99 300.941
9993.028299.35569994.813299.122710005.64302.132210016.46306.210810019.18307.3004
10027.28308.2565 10038.1311.467910045.32313.082910048.93313.996610059.75315.6171
10070.57316.799910071.47316.9141 10081.4318.177710092.22 319.393 10093.3319.5081
#Mann= 3 , 0 , 0
9883.581   0.055       09883.581   0.055       0 10093.3   0.055       0
#XS Ineff= 2 , 0
       0                               0
Bank Sta=9883.581,10093.3
Exp/Cntr=0.3,0.1

Type RM Length L Ch R = 1 ,8595.541,75.831300,75.831300,75.831300
XS GIS Cut Line= 6
980930.945922045757113.609448037980918.520288738757076.802799368
 980900.23394418757037.294448649980882.109115116757007.676829145
980831.606230192756936.196791252 980783.00688777756843.363140294
#Sta/Elev= 30
9845.282318.56389864.923317.7557 9884.13315.26689897.135314.09239919.174311.2758
9930.355309.44039937.692307.99999942.079306.95669953.802303.00339965.694296.7121
  9974.5291.73769990.397285.00029991.538284.693810002.67283.405310008.91285.6303
10014.84289.582410027.02302.8746 10039.2308.896910043.97310.109110051.29311.3737
10062.75 312.81310074.22313.444410085.68311.241810097.15 307.65110098.79308.1307
10108.34309.725110119.48316.581110127.56319.273510130.63319.998710154.74324.4558
#Mann= 3 , 0 , 0
9845.282    0.04       09845.282    0.04       010154.74    0.04       0
#XS Ineff= 2 , 0
       0                               0
Bank Sta=9845.282,10154.74
Exp/Cntr=0.3,0.1

Type RM Length L Ch R = 1 , 8519.71,102.599000,102.599000,102.599000
XS GIS Cut Line= 2
980945.715107501756979.446283117980868.892190814756853.144199774
#Sta/Elev= 23
9930.711304.07699932.087303.95329935.915303.6001 9947.62301.0846 9951.33299.9516
9959.324296.62459970.573291.91699971.029291.65959982.733285.54149989.816282.1495
9994.438280.751710006.14280.711110009.06282.112810017.85286.8619 10028.3 295.315
10029.55296.380710041.26304.430710047.55306.355610052.96307.553610064.67309.5128
10066.79309.790310076.37 310.95610078.54311.2242
#Mann= 3 , 0 , 0
9930.711    0.06       09930.711    0.06       010078.54    0.06       0
#XS Ineff= 2 , 0
       0                               0
Bank Sta=9930.711,10078.54
Exp/Cntr=0.3,0.1

Type RM Length L Ch R = 1 ,8417.111,132.292900,132.292900,132.292900
XS GIS Cut Line= 2
980986.079690844756992.467116445981008.215107501756815.383783117
#Sta/Elev= 21
 9916.03302.88649923.555301.63239933.633299.83349943.711296.81779953.789292.8869
9963.867289.18199973.945285.59489984.022278.90489987.948277.5482  9994.1275.3941
10004.18275.230710014.26280.517810024.33287.800110034.41 292.58710044.49297.0265
10054.57302.596310064.64306.044410068.57306.648710074.72307.6194 10084.8308.8916
10094.49309.9723
#Mann= 3 , 0 , 0
 9916.03    0.12       0 9916.03    0.12       010094.49    0.12       0
#XS Ineff= 2 , 0
       0                               0
Bank Sta=9916.03,10094.49
Exp/Cntr=0.3,0.1

Type RM Length L Ch R = 1 ,8284.818,132.292800,132.292800,132.292800
XS GIS Cut Line= 6
981042.966302665757024.075072463981057.867315634756992.766263632
981072.840152717756973.124307381981089.362671874756959.247601074
981135.727442904756931.102706338981178.534081773 756880.45531658
#Sta/Elev= 30
9899.162300.67779903.894299.16529909.212297.06139920.287295.19319931.362294.3649
9933.836293.82159943.601290.83949945.601289.69529956.175281.68339961.354278.0477
9971.166 271.6429974.413269.81729980.111267.82149986.557266.19289997.992261.9396
10009.31261.1044 10015.2265.280910021.16270.359510027.88277.817110033.56283.5081
10042.99286.043110047.75286.391910056.96283.386310062.07282.0937   10065281.0987
 10070.3279.6336 10078.3277.701910082.78276.860110095.02273.433110100.92273.0248
#Mann= 3 , 0 , 0
9899.162    0.12       09899.162    0.12       010100.92    0.12       0
#XS Ineff= 2 , 0
       0                               0
Bank Sta=9899.162,10100.92
Exp/Cntr=0.3,0.1

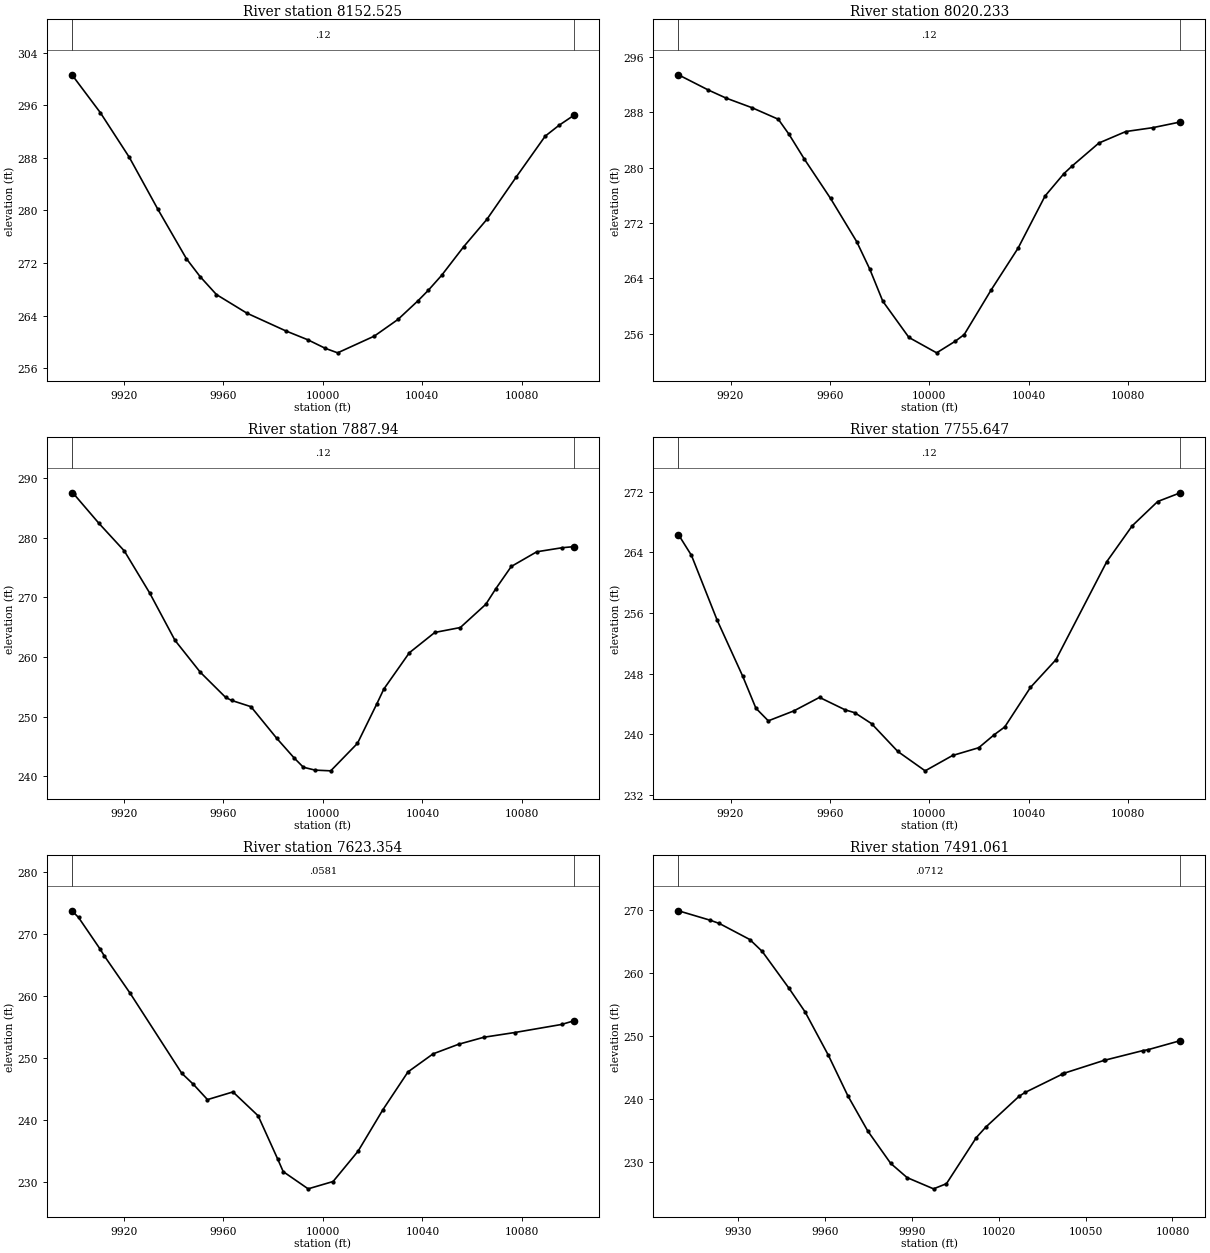
Type RM Length L Ch R = 1 ,8152.525,132.292900,132.292900,132.292900
XS GIS Cut Line= 6
981159.385467554757105.097158517981183.273370277757062.786037389
981212.996618888757020.891533106981213.824224777757019.070800152
981240.351984164756980.570422875981268.106868745756935.155492531
#Sta/Elev= 23
9899.044300.67549910.464294.90669922.123288.10079933.606280.1879 9945.09272.6583
9950.616269.92349957.179267.1934 9969.44264.3564 9985.18261.64119993.963260.3004
   10001258.995810005.94258.3134 10020.7260.863810030.23263.405210038.32266.2644
10042.38267.825510047.75270.104410056.67274.4885   10066278.654710077.72285.0605
10089.44291.321910095.02292.979610100.98294.4972
#Mann= 3 , 0 , 0
9899.044    0.12       09899.044    0.12       010100.98    0.12       0
#XS Ineff= 2 , 0
       0                               0
Bank Sta=9899.044,10100.98
Exp/Cntr=0.3,0.1

Type RM Length L Ch R = 1 ,8020.233,132.292900,132.292900,132.292900
XS GIS Cut Line= 6
981291.289938081757163.246082418981320.542145313757072.850899472
981322.738737801757068.393172496981323.831273361757066.717951302
981328.101561577757058.349280817981363.063655114756974.776791295
#Sta/Elev= 24
 9899.02293.4347 9911.07291.23139918.198290.06689928.708288.66589939.219287.0078
 9943.55284.81729949.729281.2329 9960.24275.56679970.751269.3317 9976.03265.3457
9981.261260.71599991.772255.479810002.93253.2542 10010.4 254.92610014.03255.8954
10024.87262.343710035.71268.387410046.55275.912310054.18279.163110057.38280.2316
10068.22283.570710079.06285.2333 10089.9285.791710100.99286.6142
#Mann= 3 , 0 , 0
 9899.02    0.12       0 9899.02    0.12       010100.99    0.12       0
#XS Ineff= 2 , 0
       0                               0
Bank Sta=9899.02,10100.99
Exp/Cntr=0.3,0.1

Type RM Length L Ch R = 1 , 7887.94,132.292900,132.292900,132.292900
XS GIS Cut Line= 6
981412.693828129757225.674589483981426.604950852757154.443634687
981431.458546893757138.410037381981436.862083669757126.993894455
981444.473437632757107.696327876981461.925542306757030.447983994
#Sta/Elev= 27
9899.037287.52169899.724287.34939909.913282.38959920.102277.77299930.291270.7314
 9940.48262.78859950.669257.43719960.858253.2227 9963.24 252.7179971.047251.6619
 9981.48246.33279988.366 243.093 9992.12241.51179996.837 241.02810003.14240.9079
10013.89 245.51710021.74252.188510024.51254.628610034.76260.702710045.01264.1086
10055.26  264.9310065.52268.825310069.51271.418110075.77275.167910086.02277.6313
10096.27278.312810100.94278.4918
#Mann= 3 , 0 , 0
9899.037    0.12       09899.037    0.12       010100.94    0.12       0
#XS Ineff= 2 , 0
       0                               0
Bank Sta=9899.037,10100.94
Exp/Cntr=0.3,0.1

Type RM Length L Ch R = 1 ,7755.647,132.292800,132.292800,132.292800
XS GIS Cut Line= 6
981592.471137453757240.105848737981576.723822961757176.315141376
981569.261821973757154.814740359981559.559391277 757133.74696395
981552.507736259757111.030388819981538.216834222757046.117238181
#Sta/Elev= 23
9899.033266.32749904.292263.57769914.593255.06999924.893247.67059930.207243.4506
9935.193241.78839945.493243.10229955.793244.87829966.131243.23319969.997242.8571
9976.716241.42379987.301237.75219998.295235.201610009.32 237.22310019.85238.2473
10026.07239.956110030.32240.984710040.66246.189410050.89249.831210071.37262.7627
10081.61267.485810091.85270.682410100.95271.8324
#Mann= 3 , 0 , 0
9899.033    0.12       09899.033    0.12       010100.95    0.12       0
#XS Ineff= 2 , 0
       0                               0
Bank Sta=9899.033,10100.95
Exp/Cntr=0.3,0.1

Type RM Length L Ch R = 1 ,7623.354,132.292900,132.292900,132.292900
XS GIS Cut Line= 6
981698.004524768757187.561228955981682.095653598757129.911170091
981678.565649419757107.213368161    981673.15086757047.776695087
981668.054110941757023.571790089981658.381780141756990.220751814
#Sta/Elev= 23
9899.039273.68739901.696272.60829910.334267.5349 9912.07266.40819922.444260.3963
9943.191 247.5119947.926245.70039953.565243.25169963.814244.48949973.934240.6481
9981.815 233.6729984.035231.64289994.065228.8708 10004.1230.053110014.15234.9394
10024.19 241.65810034.24247.722310044.34  250.6310054.56252.170610064.78253.3048
 10077.2254.066410095.99255.362610100.96255.9512
#Mann= 3 , 0 , 0
9899.039  0.0581       09899.039  0.0581       010100.96  0.0581       0
#XS Ineff= 2 , 0
       0                               0
Bank Sta=9899.039,10100.96
Exp/Cntr=0.3,0.1

Type RM Length L Ch R = 1 ,7491.061,49.261700,49.261700,49.261700
XS GIS Cut Line= 2
981854.569274187757103.144199789981737.381774157756975.540033132
#Sta/Elev= 25
9909.456269.89029920.513 268.3779923.603267.87049934.091265.32689938.387 263.436
9947.668257.55779953.171253.83619961.245246.91919967.955240.49419974.822234.9124
9982.739229.76859988.399227.51439997.523225.729110001.98226.546710012.31233.8825
10015.55 235.53110027.09240.444310029.13241.037410041.88243.924710042.71244.1094
10056.29246.117410056.66246.161710069.86247.693110071.44247.813510082.71249.2634
#Mann= 3 , 0 , 0
9909.456  0.0712       09909.456  0.0712       010082.71  0.0712       0
#XS Ineff= 2 , 0
       0                               0
Bank Sta=9909.456,10082.71
Exp/Cntr=0.3,0.1