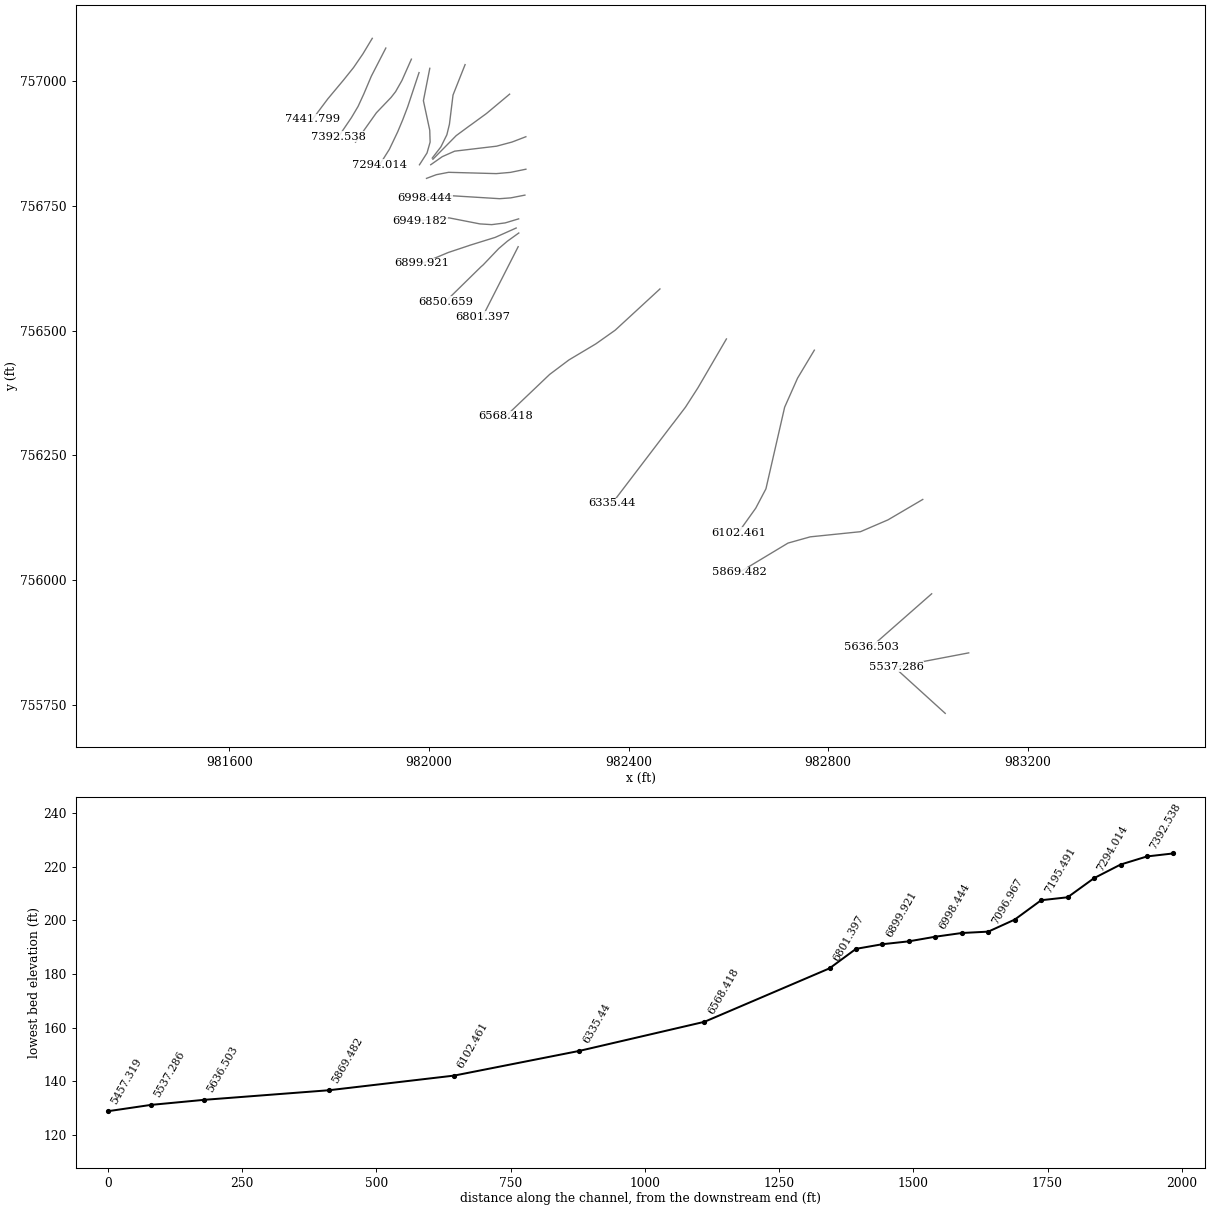
HEC-RAS study 43_ras.prj: 43

--- 43_ras.g01 (geometry) --- (continued)

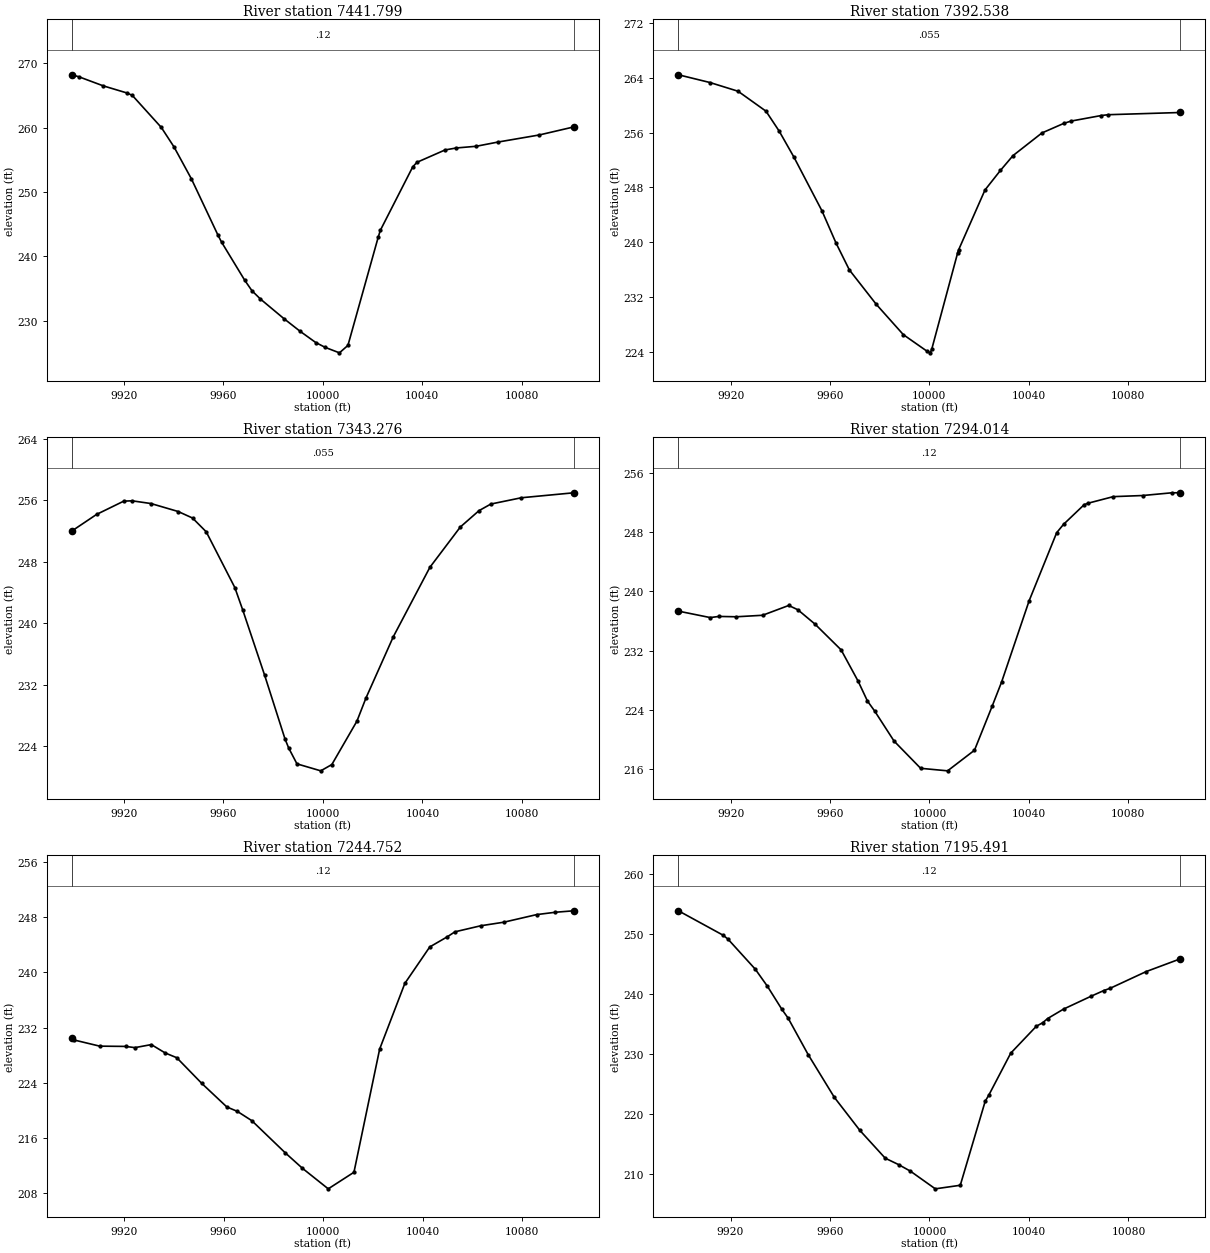
Type RM Length L Ch R = 1 ,7441.799,49.261700,49.261700,49.261700
XS GIS Cut Line= 6
981886.427226086757085.807877389981867.665692579757054.669623537
981848.926881163757027.278002711981828.627045508757001.971180452
981797.280108178756964.449170618981766.670019139756923.536228264
#Sta/Elev= 29
9899.016268.23099901.781267.92359911.634266.50589921.158265.40089923.309265.0248
9934.984260.03799940.091257.00789947.085252.04489957.801243.27129959.201242.2163
9968.557236.26499971.478234.63219974.831233.36429984.301230.31019990.807228.3437
9997.124226.5884   10001225.821810006.66 224.98510010.08226.146310022.25242.9564
10023.11244.034910036.14253.897410037.85254.617410049.18256.5426 10053.7256.8483
10061.69257.110310070.39257.763510087.08258.870410100.99260.1233
#Mann= 3 , 0 , 0
9899.016    0.12       09899.016    0.12       010100.99    0.12       0
#XS Ineff= 2 , 0
       0                               0
Bank Sta=9899.016,10100.99
Exp/Cntr=0.3,0.1

Type RM Length L Ch R = 1 ,7392.538,49.261700,49.261700,49.261700
XS GIS Cut Line= 6
981913.564981288757066.331937399981884.517241192757009.913456576
981869.513037172756974.425243297 981857.98284324756949.375346529
981844.640837721756926.865647417981818.677648554756888.608986288
#Sta/Elev= 25
9899.013264.43149911.759263.29599923.006262.03019934.254259.1182 9939.57256.2042
9945.502252.41049956.749244.5961 9962.47239.84979967.805235.95379978.661230.9205
9989.518226.5089    9999224.105210000.38223.8546   10001224.447710011.38238.4448
10011.79238.904510022.38247.621310028.58250.468810033.66252.638510045.29255.9412
10054.04257.3304   10057257.673410069.08258.479910071.91 258.60410100.98258.9273
#Mann= 3 , 0 , 0
9899.013   0.055       09899.013   0.055       010100.98   0.055       0
#XS Ineff= 2 , 0
       0                               0
Bank Sta=9899.013,10100.98
Exp/Cntr=0.3,0.1

Type RM Length L Ch R = 1 ,7343.276,49.261700,49.261700,49.261700
XS GIS Cut Line= 6
981964.816341017757044.059604563981945.833826835757001.264179014
 981933.06636757756978.791838269981924.080618505756967.336279417
981894.771562574756936.732762208981852.922140481756877.763554021
#Sta/Elev= 25
9899.041252.02549908.952254.17499919.891 255.9039923.251255.94379930.831255.5889
 9941.77254.55269947.545 253.7059953.062251.91069964.563244.66239967.789241.7057
9976.522233.28999984.773224.94549986.263223.76959989.558221.72849999.136220.8212
10003.59221.639710013.69227.288810017.31 230.28810028.31238.258610043.03247.2928
10055.29252.5415 10062.8254.664710067.55255.522510079.82256.341110100.95256.9889
#Mann= 3 , 0 , 0
9899.041   0.055       09899.041   0.055       010100.95   0.055       0
#XS Ineff= 2 , 0
       0                               0
Bank Sta=9899.041,10100.95
Exp/Cntr=0.3,0.1

Type RM Length L Ch R = 1 ,7294.014,49.261700,49.261700,49.261700
XS GIS Cut Line= 6
981980.142066034757017.133785717981957.365304481756948.498537426
981947.505991206 756922.63608305981937.354846255756898.400840289
981920.691938134756863.492961279981901.007846316756832.162022396
#Sta/Elev= 27
9899.006237.32269911.791236.45379915.332236.60659922.327236.56149932.863236.7626
9943.399238.08849947.082237.50539953.936235.57989964.472232.09229971.322 227.861
9975.066225.18479977.962 223.8399985.768219.7812 9996.47 216.10110007.32 215.759
10018.14218.541610025.28224.514610029.05227.754610040.13238.725510051.21247.9118
10053.96249.037610062.29251.701810063.96 251.90510073.99252.7822 10085.8 252.932
10097.61 253.30310100.96 253.303
#Mann= 3 , 0 , 0
9899.006    0.12       09899.006    0.12       010100.96    0.12       0
#XS Ineff= 2 , 0
       0                               0
Bank Sta=9899.006,10100.96
Exp/Cntr=0.3,0.1

Type RM Length L Ch R = 1 ,7244.752,49.261700,49.261700,49.261700
XS GIS Cut Line= 6
982001.695036932757025.755727826981988.885879003756960.808758176
982001.587892644756901.694101493 982002.34518199756877.913968956
981996.153822635756856.101355741981980.984695023756832.417617175
#Sta/Elev= 26
9899.114230.53239899.897230.21449910.267229.31469920.637229.27629924.405229.0999
9931.007229.53959936.557228.32879941.229227.63439951.279 223.9079961.329220.4965
9965.542219.85639971.388218.5012  9984.8213.84319991.706211.598410002.07208.6184
 10012.4211.022510022.73228.896310032.84238.414510042.85243.702510049.94245.1835
10052.96245.896310063.36 246.77710072.61247.291810085.79248.393110093.29248.7334
10100.74248.9487
#Mann= 3 , 0 , 0
9899.114    0.12       09899.114    0.12       010100.74    0.12       0
#XS Ineff= 2 , 0
       0                               0
Bank Sta=9899.114,10100.74
Exp/Cntr=0.3,0.1

Type RM Length L Ch R = 1 ,7195.491,49.261800,49.261800,49.261800
XS GIS Cut Line= 6
982072.410815425757033.128984868 982048.24424326756972.177422485
982041.039162347756913.560487506982035.890449254756892.510330427
982023.836783639756868.175793798982006.615568573756845.876278752
#Sta/Elev= 27
 9899.05 253.9049916.971249.84029918.961 249.1869929.945244.16769934.828241.3183
9940.677 237.4519943.168235.99459951.208229.92339961.739222.78829972.023217.2656
 9982.21212.63399987.559211.56819992.325 210.47410002.35207.521610012.39208.1174
10022.42 222.14310023.86223.151610032.68230.152210042.97234.639210045.53235.2307
10047.54235.934710053.92237.505210065.07239.666110070.07240.591710072.69240.9801
10087.15243.763710100.87245.8892
#Mann= 3 , 0 , 0
 9899.05    0.12       0 9899.05    0.12       010100.87    0.12       0
#XS Ineff= 2 , 0
       0                               0
Bank Sta=9899.05,10100.87
Exp/Cntr=0.3,0.1

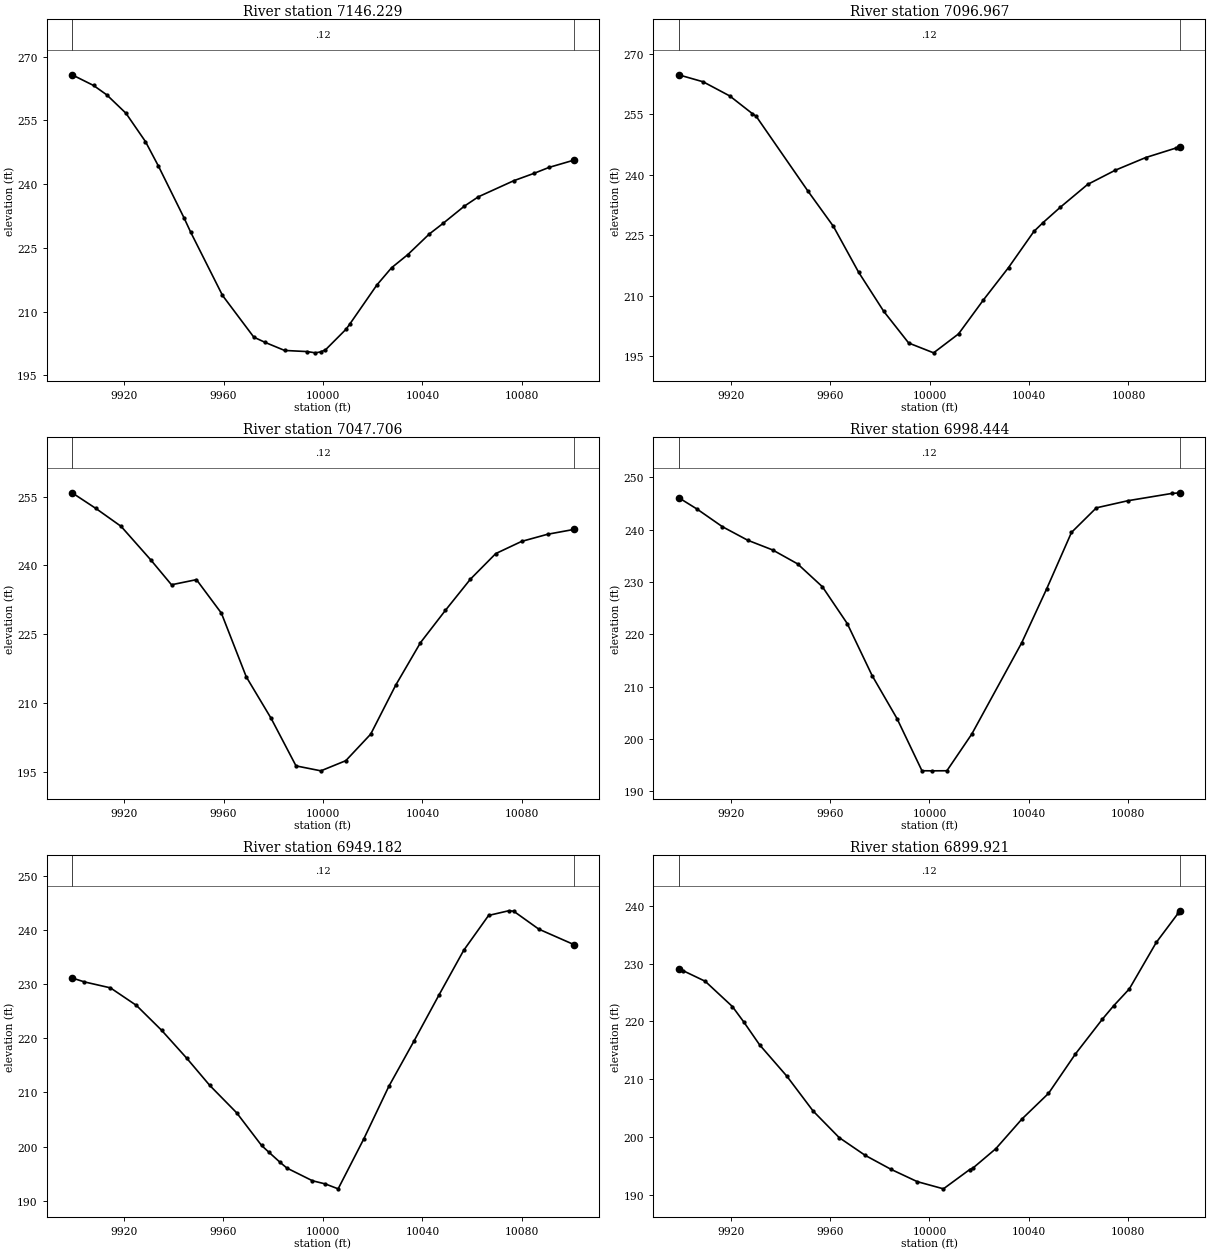
Type RM Length L Ch R = 1 ,7146.229,49.261700,49.261700,49.261700
XS GIS Cut Line= 6
982161.627615983756973.943925051982115.200006309756935.106057124
982083.311717336756911.878476042982081.648145492756910.768282942
982054.700891573756890.913736227982007.985771104756843.610691979
#Sta/Elev= 29
9899.019 265.756 9907.66263.24019912.958 261.0419920.697256.70589928.544250.0404
9933.735244.30549944.129232.00569946.772228.67539959.549213.81879972.168203.9815
9976.714202.7515 9984.54200.85829993.698200.58729996.911200.2936    9999200.5076
   10001201.000410009.26205.845710010.72207.013110021.68216.267810027.58220.3191
 10034.1223.405610042.78228.272510048.28230.754910056.84234.808210062.51237.0255
10076.74  240.8110084.95 242.55710090.97243.950910100.95245.6572
#Mann= 3 , 0 , 0
9899.019    0.12       09899.019    0.12       010100.95    0.12       0
#XS Ineff= 2 , 0
       0                               0
Bank Sta=9899.019,10100.95
Exp/Cntr=0.3,0.1

Type RM Length L Ch R = 1 ,7096.967,49.261700,49.261700,49.261700
XS GIS Cut Line= 6
982194.223706733756888.643206291982166.548526649756878.013595754
982135.431550367756869.683681958982051.490794077756859.717131846
982026.687655948756848.702604573 982003.59352154 756832.53481933
#Sta/Elev= 22
 9899.04264.75819908.921263.01959919.633259.51179928.687255.1473 9930.29254.4484
9950.994235.99769961.336227.16479971.449215.82119981.562206.11089991.616198.2352
10001.64195.801610011.66200.494210021.68208.926910031.79216.962310041.98225.9059
10045.55228.034910052.65231.9321 10063.6237.568810074.75241.099110086.96244.2303
10099.16246.596910100.88246.7961
#Mann= 3 , 0 , 0
 9899.04    0.12       0 9899.04    0.12       010100.88    0.12       0
#XS Ineff= 2 , 0
       0                               0
Bank Sta=9899.04,10100.88
Exp/Cntr=0.3,0.1

Type RM Length L Ch R = 1 ,7047.706,49.261700,49.261700,49.261700
XS GIS Cut Line= 6
982194.326303384756823.559295899982163.318901444756817.191003326
982134.976821181756814.721618428982039.313000526756817.323921356
982014.772135518756812.560214982981995.103030489 756805.17760888
#Sta/Elev= 21
9899.056255.81259908.577252.42259918.785248.4997 9930.71241.20949939.061235.7897
9949.099236.90439959.137229.60749969.141215.74629979.145206.70559989.149196.3712
9999.153195.292110009.18197.5032 10019.2203.281610029.22213.902910039.23 223.197
10049.23230.208310059.31237.0097 10069.5242.576710079.92 245.23210090.36246.7839
10100.93247.8341
#Mann= 3 , 0 , 0
9899.056    0.12       09899.056    0.12       010100.93    0.12       0
#XS Ineff= 2 , 0
       0                               0
Bank Sta=9899.056,10100.93
Exp/Cntr=0.3,0.1

Type RM Length L Ch R = 1 ,6998.444,49.261700,49.261700,49.261700
XS GIS Cut Line= 6
982192.302072922756771.630910758982164.163897778756766.145885617
982141.631132234756764.460238733982037.230990963756770.904809944
 982012.23298232756769.887893626981991.519345718756766.364538807
#Sta/Elev= 21
9899.039246.11379906.478243.92469916.667240.56079926.855237.97359936.896236.1141
9946.924233.45959956.935229.07859966.938222.04099976.941212.10679986.964203.8862
 9996.99193.9287   10001  193.9110007.03193.926410017.05200.940710037.11218.3538
10047.14228.641110057.16239.461710067.17244.157710079.95245.524810097.43246.8999
10100.96247.0342
#Mann= 3 , 0 , 0
9899.039    0.12       09899.039    0.12       010100.96    0.12       0
#XS Ineff= 2 , 0
       0                               0
Bank Sta=9899.039,10100.96
Exp/Cntr=0.3,0.1

Type RM Length L Ch R = 1 ,6949.182,49.261700,49.261700,49.261700
XS GIS Cut Line= 6
982179.762011691756724.063073898982152.771781747756715.947548871
982125.818644097756712.473272734982102.114539554756713.959925704
982040.119246203756726.079462417981981.122482878756720.520525676
#Sta/Elev= 25
9899.113231.16979904.085230.43829914.528229.3416 9924.97226.10399935.133221.4939
9945.215 216.3429954.473211.31389965.313206.24239975.332200.20019978.223 198.976
9982.833197.06029985.526196.02369995.791193.6797   10001193.087910006.12192.1862
10016.43201.412910026.51211.136910036.58219.469910046.62227.974610056.62236.2808
10066.63  242.7310074.69243.588810076.69243.519110086.83240.192110100.92237.3421
#Mann= 3 , 0 , 0
9899.113    0.12       09899.113    0.12       010100.92    0.12       0
#XS Ineff= 2 , 0
       0                               0
Bank Sta=9899.113,10100.92
Exp/Cntr=0.3,0.1

Type RM Length L Ch R = 1 ,6899.921,49.261700,49.261700,49.261700
XS GIS Cut Line= 6
982174.793477365 756705.71078525982132.759826464756686.932188905
982081.272612591756670.933943843982079.404508921756670.219668912
982038.565799272756656.609442197981986.056701822756634.648945178
#Sta/Elev= 25
9899.047 229.0549900.789228.78789909.773226.94419920.726 222.5779925.305219.9149
9931.678215.96329942.631210.5604 9953.21204.53939963.682199.95779974.154196.8907
9984.625  194.469995.097192.354610005.64191.110310016.18194.431310017.51194.6955
10026.72198.042210037.26203.178110047.91207.584310058.75214.394310069.59220.3952
10074.14 222.71610080.43225.617810091.27233.639110100.05238.664510100.96239.1113
#Mann= 3 , 0 , 0
9899.047    0.12       09899.047    0.12       010100.96    0.12       0
#XS Ineff= 2 , 0
       0                               0
Bank Sta=9899.047,10100.96
Exp/Cntr=0.3,0.1

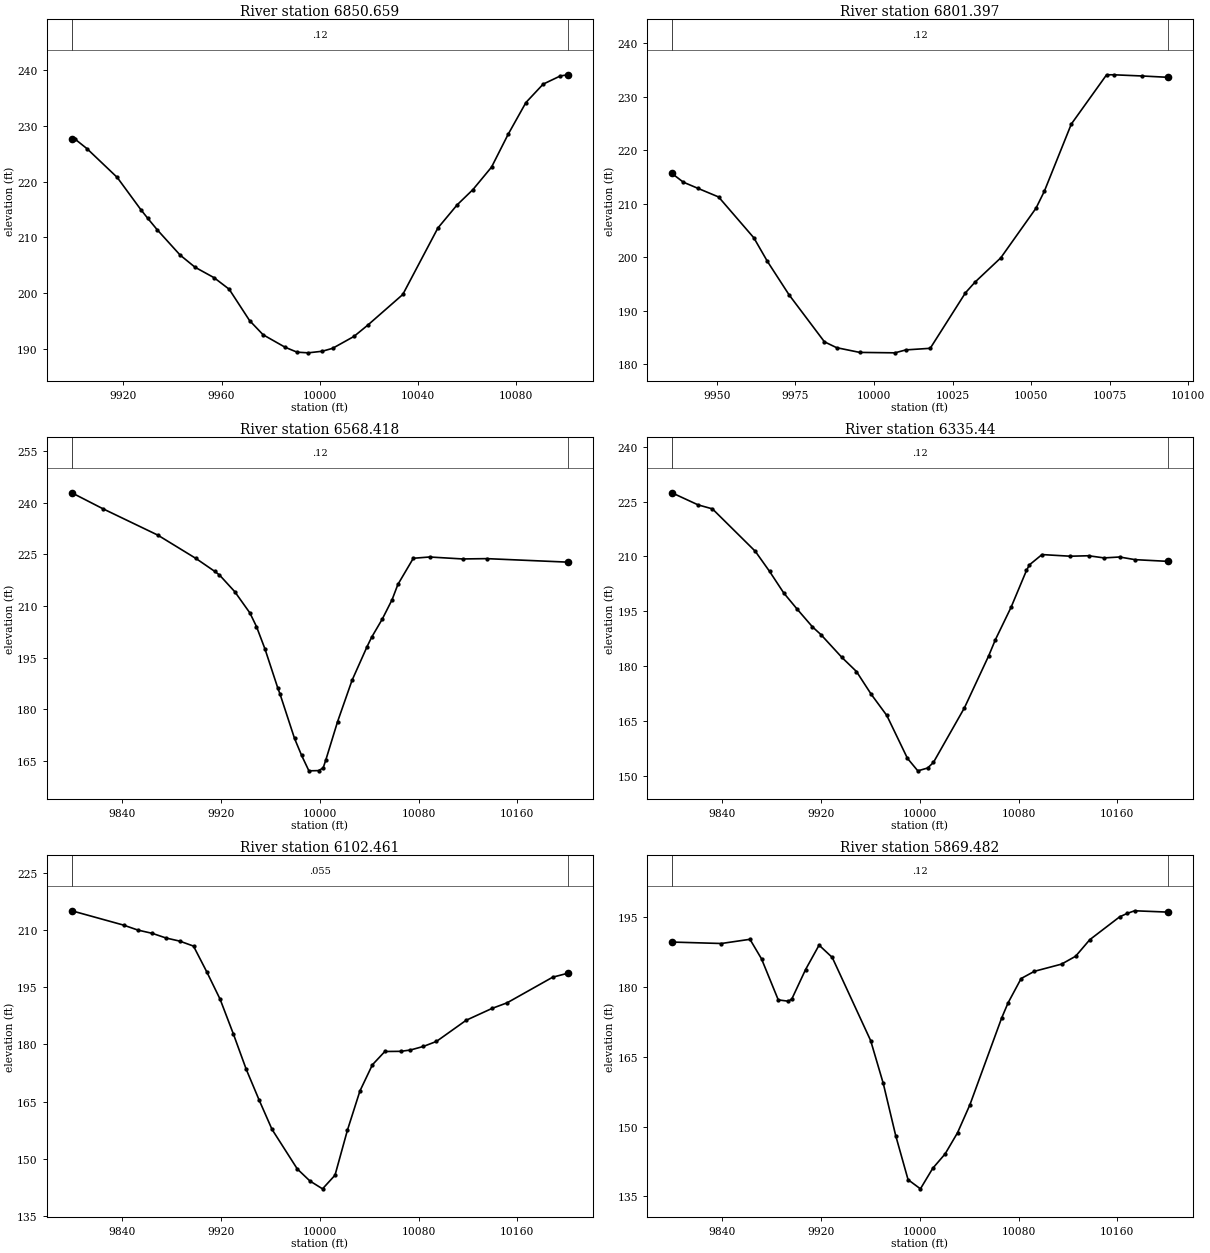
Type RM Length L Ch R = 1 ,6850.659,49.261700,49.261700,49.261700
XS GIS Cut Line= 6
982180.023332859756695.712297628982157.110159225756679.276056096
982139.802301521756664.509992247 982108.55894782756631.729277525
982104.233892111 756627.96312461982032.835795088756557.979661502
#Sta/Elev= 30
9899.027227.69079900.249227.61959905.209225.88079917.516220.74299927.225214.9288
9929.999213.40839933.814211.37949943.144206.85479949.221204.68139956.937202.8194
9963.114200.75279971.431195.14159976.928192.61099985.925190.37229990.743189.5014
9995.261189.3797   10001189.663410005.23190.187910013.93192.314610019.52194.3219
 10033.8199.808310048.09211.691510055.94215.833110062.38218.569310069.94222.5791
10076.66228.409810083.94234.122410090.95237.409310097.95238.875210100.98239.0837
#Mann= 3 , 0 , 0
9899.027    0.12       09899.027    0.12       010100.98    0.12       0
#XS Ineff= 2 , 0
       0                               0
Bank Sta=9899.027,10100.98
Exp/Cntr=0.3,0.1

Type RM Length L Ch R = 1 ,6801.397,232.978800,232.978800,232.978800
XS GIS Cut Line= 2
982178.788024157756668.248366445982107.173440814756527.623366445
#Sta/Elev= 23
9935.707215.66329939.353214.02119944.055212.85649950.575211.25669961.797203.6123
9966.091199.22249973.019192.94119984.241184.17799988.127183.07839995.463182.1951
10006.69182.112410010.16182.661510017.91182.959910029.13193.3427 10032.2195.3549
10040.35199.867110051.57209.158910054.23212.3389 10062.8224.885210074.02234.0945
10076.27234.100110085.24233.877310093.52233.6277
#Mann= 3 , 0 , 0
9935.707    0.12       09935.707    0.12       010093.52    0.12       0
#XS Ineff= 2 , 0
       0                               0
Bank Sta=9935.707,10093.52
Exp/Cntr=0.3,0.1

Type RM Length L Ch R = 1 ,6568.418,232.978800,232.978800,232.978800
XS GIS Cut Line= 6
982462.897922701756583.598903916982373.194869156756500.950745585
982334.433850884756473.539982748982280.530772825756441.380758193
982241.873587869756412.320476922 982154.09279495756328.742664668
#Sta/Elev= 30
9799.054242.9011 9824.08238.30079868.726230.61429899.485223.87139914.865220.0845
9918.716219.03699931.129214.17639943.377208.00879948.718204.04899955.625197.5224
9966.037186.14539967.873184.36659979.549171.56369985.244166.67089991.191162.1593
    9999162.226710002.76163.014310004.99165.423110014.44176.453710026.12188.4177
10038.26 198.17410041.96200.906810050.77206.3095 10058.6211.858210063.28216.2733
10075.79223.881210088.92224.255210115.74223.685810135.29223.777210200.95222.7612
#Mann= 3 , 0 , 0
9799.054    0.12       09799.054    0.12       010200.95    0.12       0
#XS Ineff= 2 , 0
       0                               0
Bank Sta=9799.054,10200.95
Exp/Cntr=0.3,0.1

Type RM Length L Ch R = 1 , 6335.44,232.978900,232.978900,232.978900
XS GIS Cut Line= 6
982596.095702495 756483.40104054982539.119424331756385.673756883
982514.058741572756346.699670281982489.508755134756314.472442503
982488.219089973756312.943794809 982367.02121634 756153.87509514
#Sta/Elev= 30
9799.028227.43689820.328224.11879831.903223.02849866.629211.42119878.205205.9119
 9889.78199.96659900.476195.61719912.952190.73039919.768188.6292 9936.73182.3931
9948.619178.50679960.624172.24569973.195166.48269989.938154.73769998.337151.3101
10006.31152.082910010.99153.607510036.13168.566910055.81182.822310061.27187.2621
10073.85196.036310086.42206.179110088.81 207.70910098.99210.520210121.81210.0708
10136.71210.195910149.28209.605310161.85209.854410174.42209.127110200.98208.6611
#Mann= 3 , 0 , 0
9799.028    0.12       09799.028    0.12       010200.98    0.12       0
#XS Ineff= 2 , 0
       0                               0
Bank Sta=9799.028,10200.98
Exp/Cntr=0.3,0.1

Type RM Length L Ch R = 1 ,6102.461,232.978800,232.978800,232.978800
XS GIS Cut Line= 6
982772.296699548756460.949007448982738.673161482756404.869130138
 982712.77089937756346.607404518982675.294490536756183.095696007
982654.868363976756144.311869033982619.697872318756095.042795305
#Sta/Elev= 30
9799.053215.03959840.968 211.2839852.628209.9754 9864.44209.10399875.425207.8954
9886.556 207.0779897.659205.77629908.431198.99949919.203191.84219929.925182.7539
9940.387 173.4439950.848165.37329961.244157.70739981.753147.31049992.007144.1492
10002.18142.101610012.28145.676410022.37157.515110032.47167.769210042.56174.6361
10052.66178.127510065.58  178.17 10073.4 178.51910083.93179.460710094.46180.7707
10118.56 186.32410139.52189.431910151.74190.9044 10188.6197.614510200.84198.6524
#Mann= 3 , 0 , 0
9799.053   0.055       09799.053   0.055       010200.84   0.055       0
#XS Ineff= 2 , 0
       0                               0
Bank Sta=9799.053,10200.84
Exp/Cntr=0.3,0.1

Type RM Length L Ch R = 1 ,5869.482,232.978800,232.978800,232.978800
XS GIS Cut Line= 6
 982989.53557066756161.788863639 982919.88838617756120.871834788
982864.728817751 756097.17775188982764.082261872756086.846514976
982719.537696471756074.352336127982622.929229668756016.211706299
#Sta/Elev= 30
9799.113189.57539839.167189.26549862.363190.1663 9871.74 185.9779885.303177.1717
9893.553176.88159896.378177.41169907.453183.6886 9918.37188.91479929.032186.2766
9960.155168.4383 9970.38159.23929980.461148.03669990.467138.600210000.47136.6392
10010.47  141.0510020.48144.131510030.53148.670610040.59154.698810066.24 173.259
 10071.5176.544210082.06181.753310092.82183.301710114.79 184.84210126.19186.5289
10137.67190.084810161.85194.981310168.04195.728110174.03196.284610200.92195.9996
#Mann= 3 , 0 , 0
9799.113    0.12       09799.113    0.12       010200.92    0.12       0
#XS Ineff= 2 , 0
       0                               0
Bank Sta=9799.113,10200.92
Exp/Cntr=0.3,0.1

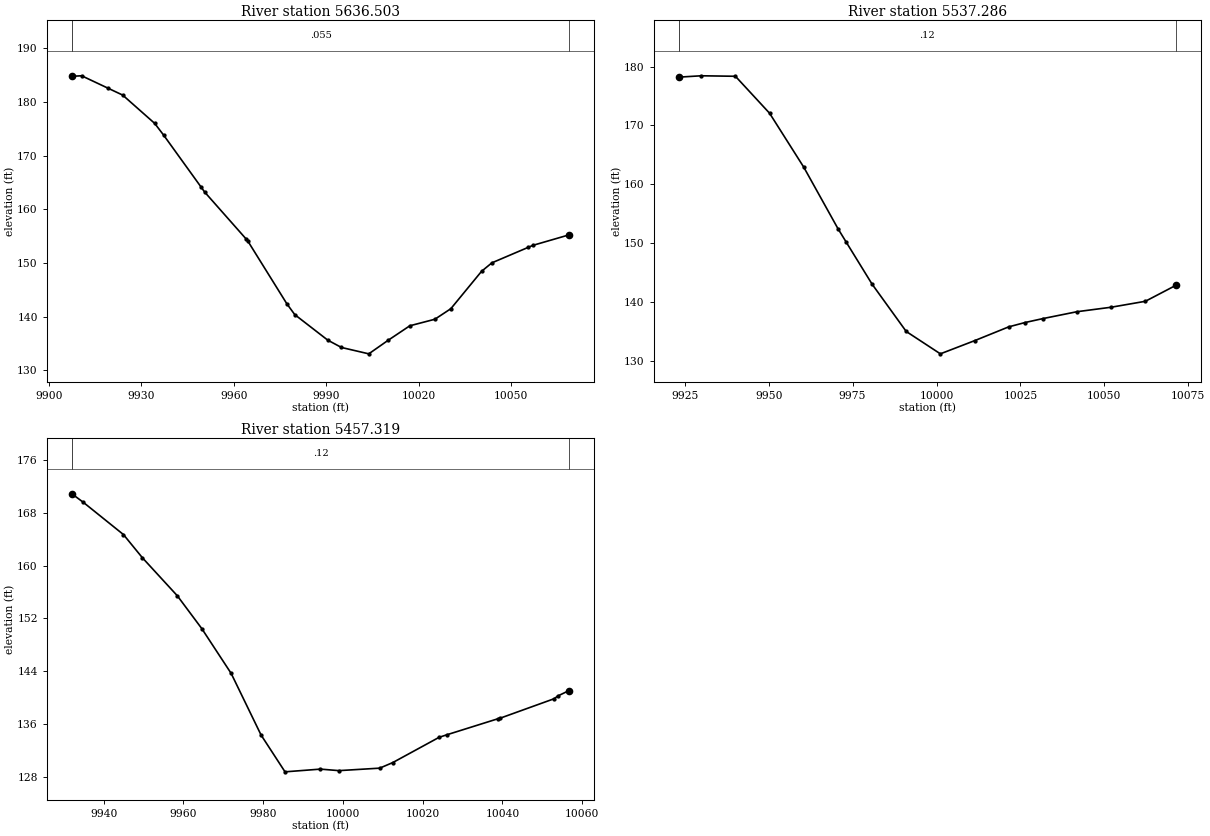
Type RM Length L Ch R = 1 ,5636.503,99.216700,99.216700,99.216700
XS GIS Cut Line= 2
983007.388785362755972.738675952982886.151055038755866.230763286
#Sta/Elev= 24
9907.416184.79089910.596184.88589919.141 182.5749923.906181.28869934.293176.0116
9937.217173.80969949.445164.06389950.528163.19689963.839154.54399964.596153.9975
 9977.15142.40689979.748140.3606 9990.46135.5996  9994.9134.237210003.77133.0498
10010.05135.577110017.08138.2789 10025.2139.496310030.39141.464110040.35 148.427
 10043.7150.012210055.51152.904710057.01153.273710068.79155.2368
#Mann= 3 , 0 , 0
9907.416   0.055       09907.416   0.055       010068.79   0.055       0
#XS Ineff= 2 , 0
       0                               0
Bank Sta=9907.416,10068.79
Exp/Cntr=0.3,0.1

Type RM Length L Ch R = 1 ,5537.286,79.967800,79.967800,79.967800
XS GIS Cut Line= 2
983081.604405344755854.333602846982936.005822629755826.573561773
#Sta/Elev= 18
 9923.17 178.2259929.893178.45859940.074178.37389950.254172.08369960.434162.9128
9970.614152.46779973.006150.23669980.794143.01529990.974134.960210001.15131.1547
10011.33133.389510021.51135.7427 10026.4136.483310031.69137.149910041.87138.3226
10052.06139.084110062.24140.094610071.39 142.825
#Mann= 3 , 0 , 0
 9923.17    0.12       0 9923.17    0.12       010071.39    0.12       0
#XS Ineff= 2 , 0
       0                               0
Bank Sta=9923.17,10071.39
Exp/Cntr=0.3,0.1

Type RM Length L Ch R = 1 ,5457.319,36.917500,36.917500,36.917500
XS GIS Cut Line= 2
983034.582295001755733.095872477982942.237668604  755816.9425271
#Sta/Elev= 20
9932.028170.86769934.861169.59619944.971164.69699949.737161.17739958.478155.4397
9964.613150.47519971.985143.69199979.489 134.3659985.492128.80139994.365129.2133
9998.999128.983810009.24  129.3610012.51130.201110024.12 134.01810026.01134.3951
10038.99136.852610039.52136.933410053.03139.871410053.87140.268910056.76141.1036
#Mann= 3 , 0 , 0
9932.028    0.12       09932.028    0.12       010056.76    0.12       0
#XS Ineff= 2 , 0
       0                               0
Bank Sta=9932.028,10056.76
Exp/Cntr=0.3,0.1