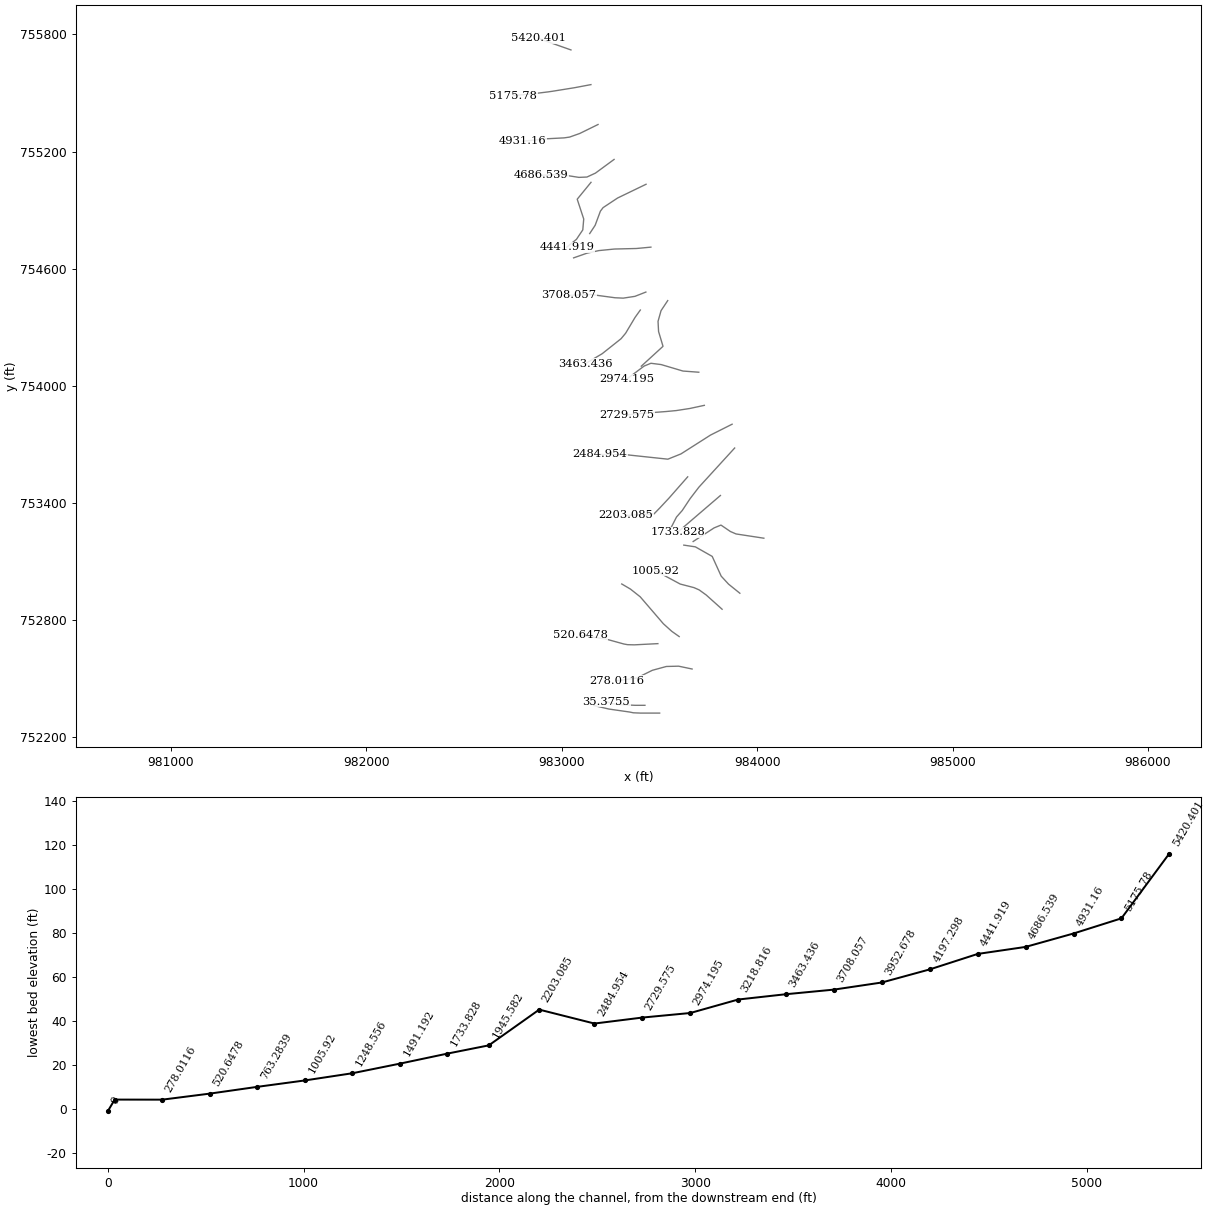
HEC-RAS study 43_ras.prj: 43

--- 43_ras.g01 (geometry) --- (continued)

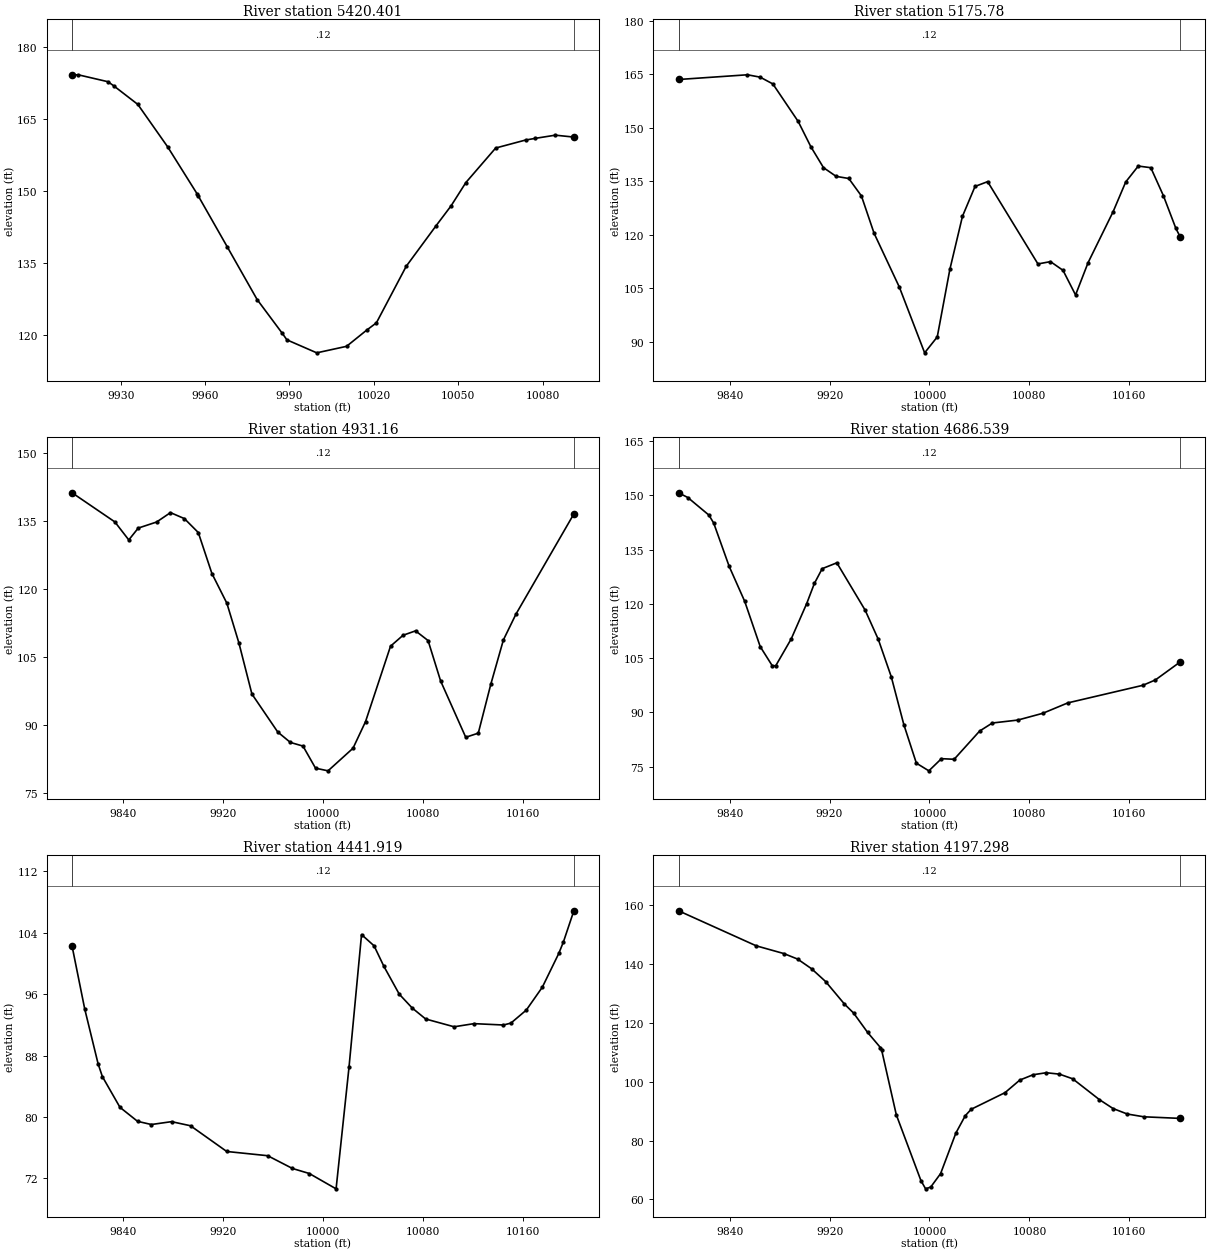
Type RM Length L Ch R = 1 ,5420.401,244.620600,244.620600,244.620600
XS GIS Cut Line= 2
983047.045986891755720.065649107982878.786146164  755779.5514514
#Sta/Elev= 25
9912.681174.09059914.851174.15019925.458172.70459927.485171.85869936.064167.9851
9946.671159.16369957.277149.26549957.486149.02839967.884 138.3469978.491127.4041
9987.488 120.3349989.097119.00919999.704116.308910010.31117.663610017.49121.0439
10020.92 122.54810031.52 134.30710042.13142.736110047.49 146.89310052.74151.7311
10063.34158.912110073.95160.571710077.49160.930510084.56161.587710091.15161.1884
#Mann= 3 , 0 , 0
9912.681    0.12       09912.681    0.12       010091.15    0.12       0
#XS Ineff= 2 , 0
       0                               0
Bank Sta=9912.681,10091.15
Exp/Cntr=0.3,0.1

Type RM Length L Ch R = 1 , 5175.78,244.620500,244.620500,244.620500
XS GIS Cut Line= 6
983149.253817424 755542.52913908983065.871001474755526.774019162
982952.200089393755508.469364326982929.671411043755505.230665251
982864.211127053755497.126269826 982751.46804847755486.163151579
#Sta/Elev= 30
9799.006163.5316 9854.22 164.8569864.397 164.1889874.574162.28589894.876151.7504
9905.005144.66989915.133138.79569925.262136.35169935.391135.7548 9945.52130.8622
9955.649120.39899975.906105.27859996.16486.8341510006.2791.2934710016.38110.2673
10026.47125.148810036.54133.525410046.62134.870610086.93111.778210096.98112.4281
10107.02109.985410117.07103.075910127.12112.151310147.21126.479910157.26 134.786
10167.31139.244410177.35138.7848 10187.4130.965210197.45121.7385   10201 119.299
#Mann= 3 , 0 , 0
9799.006    0.12       09799.006    0.12       0   10201    0.12       0
#XS Ineff= 2 , 0
       0                               0
Bank Sta=9799.006,10201
Exp/Cntr=0.3,0.1

Type RM Length L Ch R = 1 , 4931.16,244.620600,244.620600,244.620600
XS GIS Cut Line= 6
983185.788093189755338.324992061983091.743341188755292.234907257
983040.248395012755273.935704867 983012.96221147755269.880379108
 982922.25507332 755265.11251619982798.859466654755252.290412073
#Sta/Elev= 30
9799.058 141.2489833.344134.82199844.481130.8526 9852.06133.46329866.753134.7988
 9877.89136.87359889.026135.55459900.162132.48049911.065123.4483 9923.06116.8868
9932.643 108.1819943.11396.875949963.80788.498599973.91786.205179984.02785.39755
9994.06380.5283610004.0879.94037 10024.184.9274510034.1290.7952610054.14107.4233
10064.16109.829910074.17 110.80510084.21108.664910094.2799.7493610114.3887.34061
10124.4388.2500410134.48 99.055910144.54108.802810154.59114.487610200.98136.5883
#Mann= 3 , 0 , 0
9799.058    0.12       09799.058    0.12       010200.98    0.12       0
#XS Ineff= 2 , 0
       0                10068.57       0
Bank Sta=9799.058,10200.98
Exp/Cntr=0.3,0.1

Type RM Length L Ch R = 1 ,4686.539,244.620500,244.620500,244.620500
XS GIS Cut Line= 6
 983267.70670474755159.403391633983172.491480753755089.450072037
983128.874992533755069.259147588983087.557418656755067.518122447
982992.153277362755082.521827246982895.072148131 755078.46527162
#Sta/Elev= 30
9799.105150.69949806.542149.38939823.432144.52929827.281142.3095 9839.69 130.325
9852.099120.68569864.507108.17839874.102102.92429876.916102.86979889.325110.2961
9901.734 120.0729907.881 125.6369914.142129.72189925.858131.34019948.541118.2518
9959.081110.17159969.44199.868019979.51886.623649989.55875.958079999.55973.83884
10009.6377.2025310019.8277.03593 10040.284.8296610050.3987.0606810070.7687.87189
10090.83  89.74810110.8892.6270710170.9497.4827510180.9698.9651310200.93103.9679
#Mann= 3 , 0 , 0
9799.105    0.12       09799.105    0.12       010200.93    0.12       0
#XS Ineff= 2 , 0
       0                               0
Bank Sta=9799.105,10200.93
Exp/Cntr=0.3,0.1

Type RM Length L Ch R = 1 ,4441.919,244.620600,244.620600,244.620600
XS GIS Cut Line= 6
983149.655544527755042.219001729  983079.0250998 754955.72282758
983112.317294647754854.374871652983107.616291553754798.723140355
983075.110958263754750.286199994983025.288989117754710.064094961
#Sta/Elev= 30
9799.336102.26289809.49994.049669820.15786.936829823.577 85.27349837.65581.26617
9851.73379.441769862.779 79.02799878.92179.400949894.089 78.8657 9923.0775.51573
9955.81974.965299975.639 73.30319989.12872.6465810010.5570.6499410020.8786.45659
10030.91103.767210040.93 102.306 10048.899.6274810061.0996.0042210071.4494.20396
10082.2192.7715810104.9691.7576910120.8992.1666410144.4391.9883710150.4192.23697
10162.6993.9271110175.5396.9098910188.72101.315210192.43102.817210200.77 106.867
#Mann= 3 , 0 , 0
9799.336    0.12       09799.336    0.12       010200.77    0.12       0
#XS Ineff= 2 , 0
       0                               0
Bank Sta=9799.336,10200.77
Exp/Cntr=0.3,0.1

Type RM Length L Ch R = 1 ,4197.298,244.620500,244.620500,244.620500
XS GIS Cut Line= 6
983431.401167013755032.272069603983285.861710708754961.935546796
983211.470587259754912.641694095983197.753728007754894.652683832
983170.803763074754822.094988601983142.995881419754779.824300628
#Sta/Elev= 30
9799.033158.15129861.273146.23359883.343143.60879894.378 141.7379905.569138.4446
9916.788134.10529931.885126.44399939.227123.38119950.447116.79959960.699111.6497
 9961.71110.74929973.435 88.77929993.13766.433829996.885 63.6194   1000164.23326
10008.8968.7937410021.1582.6068910028.6488.4771910033.41 90.6776 10060.596.32098
10072.32100.596910082.93102.4021 10093.5103.094610104.07102.611910114.64101.0362
10136.0693.9503910147.0190.9202510158.3789.0580910171.64 88.111910200.8787.56695
#Mann= 3 , 0 , 0
9799.033    0.12       09799.033    0.12       010200.87    0.12       0
#XS Ineff= 2 , 0
       0                               0
Bank Sta=9799.033,10200.87
Exp/Cntr=0.3,0.1

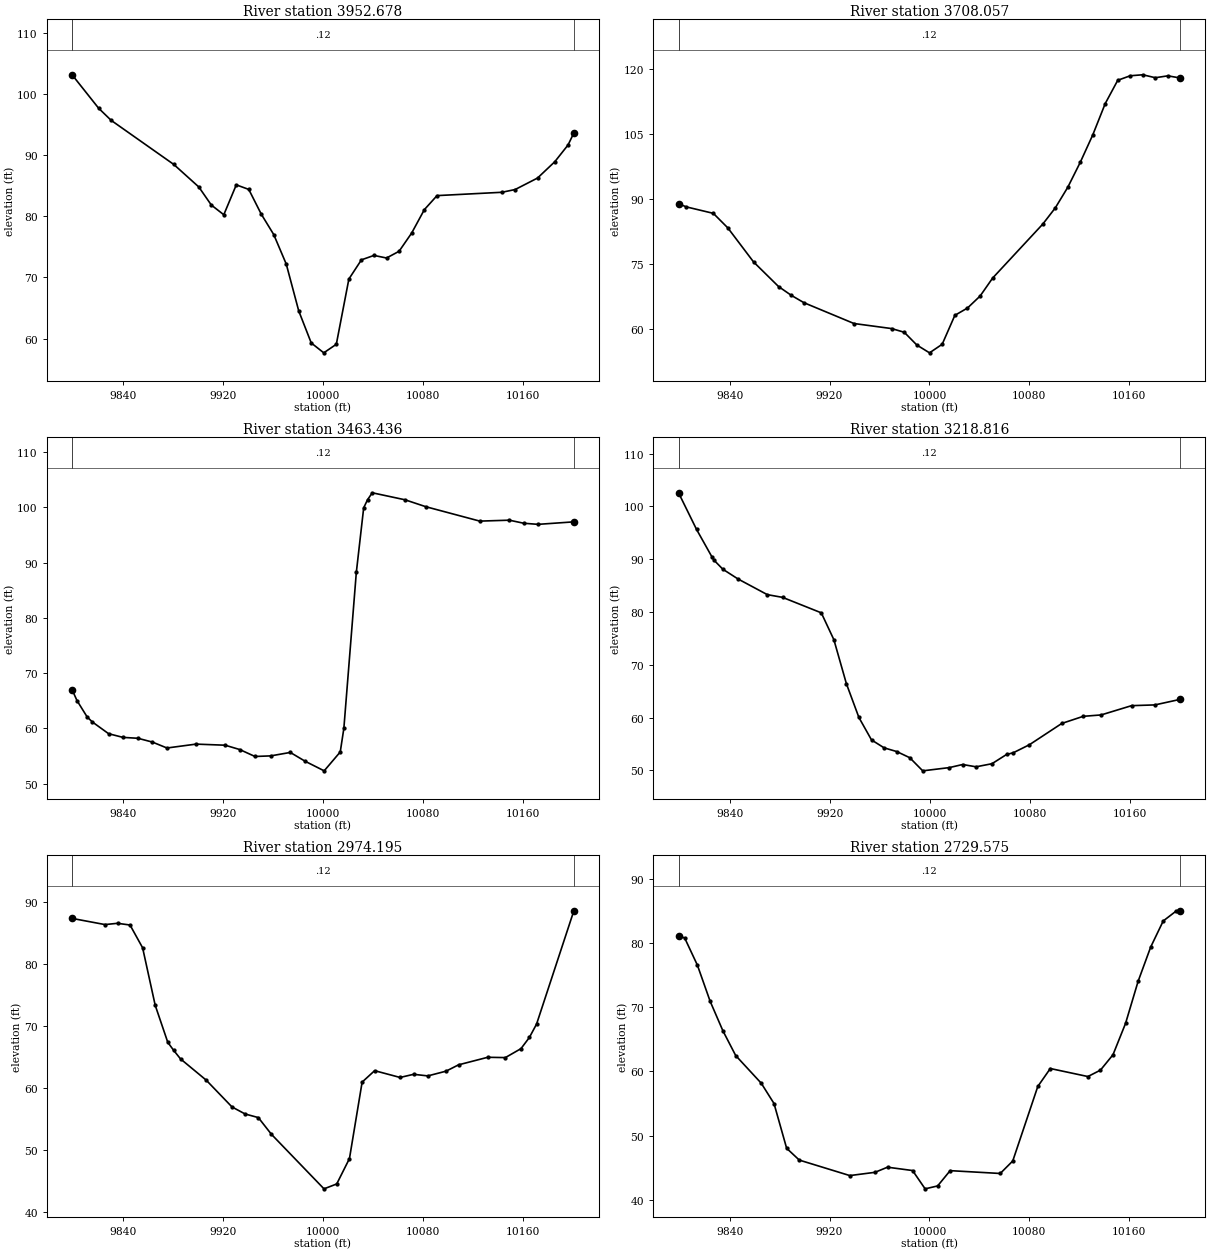
Type RM Length L Ch R = 1 ,3952.678,244.620600,244.620600,244.620600
XS GIS Cut Line= 6
983456.191431778754710.323324445983382.235994141754703.358638019
983269.504806353754700.605858661983189.729206322754692.633124862
983129.286625681754679.464228467983060.596783883754655.366991706
#Sta/Elev= 30
9799.041103.17649820.32697.69915 9830.3795.714259880.56188.492869900.56784.81029
 9910.5781.856369920.57380.266239930.57685.159489940.57984.411879950.582 80.3634
9960.58577.016539970.58872.199729980.59164.52723 9990.6159.2807510000.6557.66278
 10010.7 59.065910020.7569.7423310030.8172.8848110040.86 73.608410050.9173.18497
10060.96 74.284410071.0677.2746310081.2281.1045110091.3783.3985110143.3183.94325
10153.9184.3909810171.8686.27279 10185.788.94753 10196.391.6852210200.9693.64974
#Mann= 3 , 0 , 0
9799.041    0.12       09799.041    0.12       010200.96    0.12       0
#XS Ineff= 2 , 0
       0                               0
Bank Sta=9799.041,10200.96
Exp/Cntr=0.3,0.1

Type RM Length L Ch R = 1 ,3708.057,244.620600,244.620600,244.620600
XS GIS Cut Line= 6
983430.475184708754480.271020322983374.600447884754458.357672357
983314.521357888754449.175274763983272.467151376754451.124934251
983149.994823255754467.668896517983035.047544975754463.549363754
#Sta/Elev= 30
9799.09788.882199805.08588.129359826.95886.619199838.602 83.25279859.17475.40691
9879.19769.726449889.41367.694739899.52765.997029939.61261.191739969.72760.02616
9979.84859.174769989.96956.22233 10000.154.4248610010.2456.4038410020.3863.07855
10030.5164.7702310040.6267.5380210050.6671.6910710090.8284.1474310100.8287.88016
10110.8292.6375810120.8298.4019910130.82104.716410140.82111.963810150.83117.3318
10160.86118.3771 10170.9118.602810180.93117.924610190.96118.357710200.95117.8575
#Mann= 3 , 0 , 0
9799.097    0.12       09799.097    0.12       010200.95    0.12       0
#XS Ineff= 2 , 0
       0 9960.43                       0
Bank Sta=9799.097,10200.95
Exp/Cntr=0.3,0.1

Type RM Length L Ch R = 1 ,3463.436,244.620500,244.620500,244.620500
XS GIS Cut Line= 6
983402.013159183754388.200859044983375.226966019 754350.70373437
983326.801285804 754269.50336992983303.566254022754241.487768629
983206.804352217754164.596620332983119.744505527754113.167935587
#Sta/Elev= 30
9799.106  67.0149803.03965.041379811.17162.081579815.32961.174249828.37459.04739
9839.90858.381349851.82858.221229863.47257.532489875.11556.463029898.402 57.1662
9921.68856.967239933.33156.188349945.58254.930279958.21855.038069973.88255.66106
 9985.85 54.055910001.01 52.333710013.8855.7463510016.7760.0160410026.7588.21055
10032.6599.8901810035.75101.353910039.52102.607910065.81101.336510082.46100.0862
10125.6297.4852510149.3197.65298 10160.997.0954910172.2796.8997410200.9797.35169
#Mann= 3 , 0 , 0
9799.106    0.12       09799.106    0.12       010200.97    0.12       0
#XS Ineff= 2 , 0
       0 9945.15                       0
Bank Sta=9799.106,10200.97
Exp/Cntr=0.3,0.1

Type RM Length L Ch R = 1 ,3218.816,244.620600,244.620600,244.620600
XS GIS Cut Line= 6
983542.235366326754436.501420035983508.091198619754385.045667696
983492.720264551754330.321789964   983495.455055754278.281053991
983518.191322021 754202.40208117983407.076819951754100.813365559
#Sta/Elev= 30
9799.174102.59199813.59295.646579826.12790.347759827.75689.771469834.65888.10174
9846.76186.26292  9870.283.292839882.393 82.77799913.36779.846879923.44674.75042
9933.451 66.42399943.46660.019099953.54355.77023 9963.6254.26835 9973.7953.56222
9984.15252.397619994.51549.9127310015.7350.5247210026.4551.1118610037.1750.67662
10049.8951.2604510061.5653.0107210066.9653.33901 10079.954.8645410105.7858.89479
 10122.960.2395610137.2360.50427 10161.662.2627210180.24 62.402210200.58 63.4608
#Mann= 3 , 0 , 0
9799.174    0.12       09799.174    0.12       010200.58    0.12       0
#XS Ineff= 2 , 0
       0                               0
Bank Sta=9799.174,10200.58
Exp/Cntr=0.3,0.1

Type RM Length L Ch R = 1 ,2974.195,244.620500,244.620500,244.620500
XS GIS Cut Line= 6
983701.357832068754069.826740186983620.450642604754075.823790636
983508.788570565754108.975303017983456.347987088754115.628922105
983421.618963599754101.459575683983331.113550343754033.634864924
#Sta/Elev= 30
9799.07987.303729825.44986.309739835.45386.514389845.47786.238399855.557 82.5755
9865.63773.322539875.71667.356449880.30266.099679885.90264.69358 9906.4561.27671
9927.11856.960029937.65655.824149948.19355.248499958.73152.5468210000.7843.77871
10010.9744.5648610021.1748.6534710031.3160.9561710041.3262.7968310061.6961.70474
10072.5862.2131610083.9161.9539210098.5162.71907 10108.563.7354910131.8664.95092
10145.9964.9007910158.4966.3428310165.2168.1397410170.9870.2986610200.83 88.5306
#Mann= 3 , 0 , 0
9799.079    0.12       09799.079    0.12       010200.83    0.12       0
#XS Ineff= 2 , 0
       0                               0
Bank Sta=9799.079,10200.83
Exp/Cntr=0.3,0.1

Type RM Length L Ch R = 1 ,2729.575,244.620600,244.620600,244.620600
XS GIS Cut Line= 6
983729.762422847753900.238312284983655.289479938753884.171569668
983585.807906112753873.448827664983532.566782031753868.419144461
 983405.16312475753858.825988883983331.373612034 753850.81323828
#Sta/Elev= 30
9799.03181.075939803.90380.804479814.13376.555919824.36470.916639834.59466.31703
9844.82462.472239865.28458.164089875.51155.000199885.62948.028749895.74746.19012
9936.22143.775879956.37844.282069966.42245.081499986.51144.560259996.55641.71022
10006.58  42.16310016.6144.5440810056.7344.1032210066.7646.0510810086.8257.65801
10096.8460.4517510126.9359.2028710136.9960.1972210147.0562.5962210157.1167.47744
10167.1774.0323510177.2379.3635210187.2983.4347210197.3484.9338710200.9985.02281
#Mann= 3 , 0 , 0
9799.031    0.12       09799.031    0.12       010200.99    0.12       0
#XS Ineff= 2 , 0
       0                               0
Bank Sta=9799.031,10200.99
Exp/Cntr=0.3,0.1

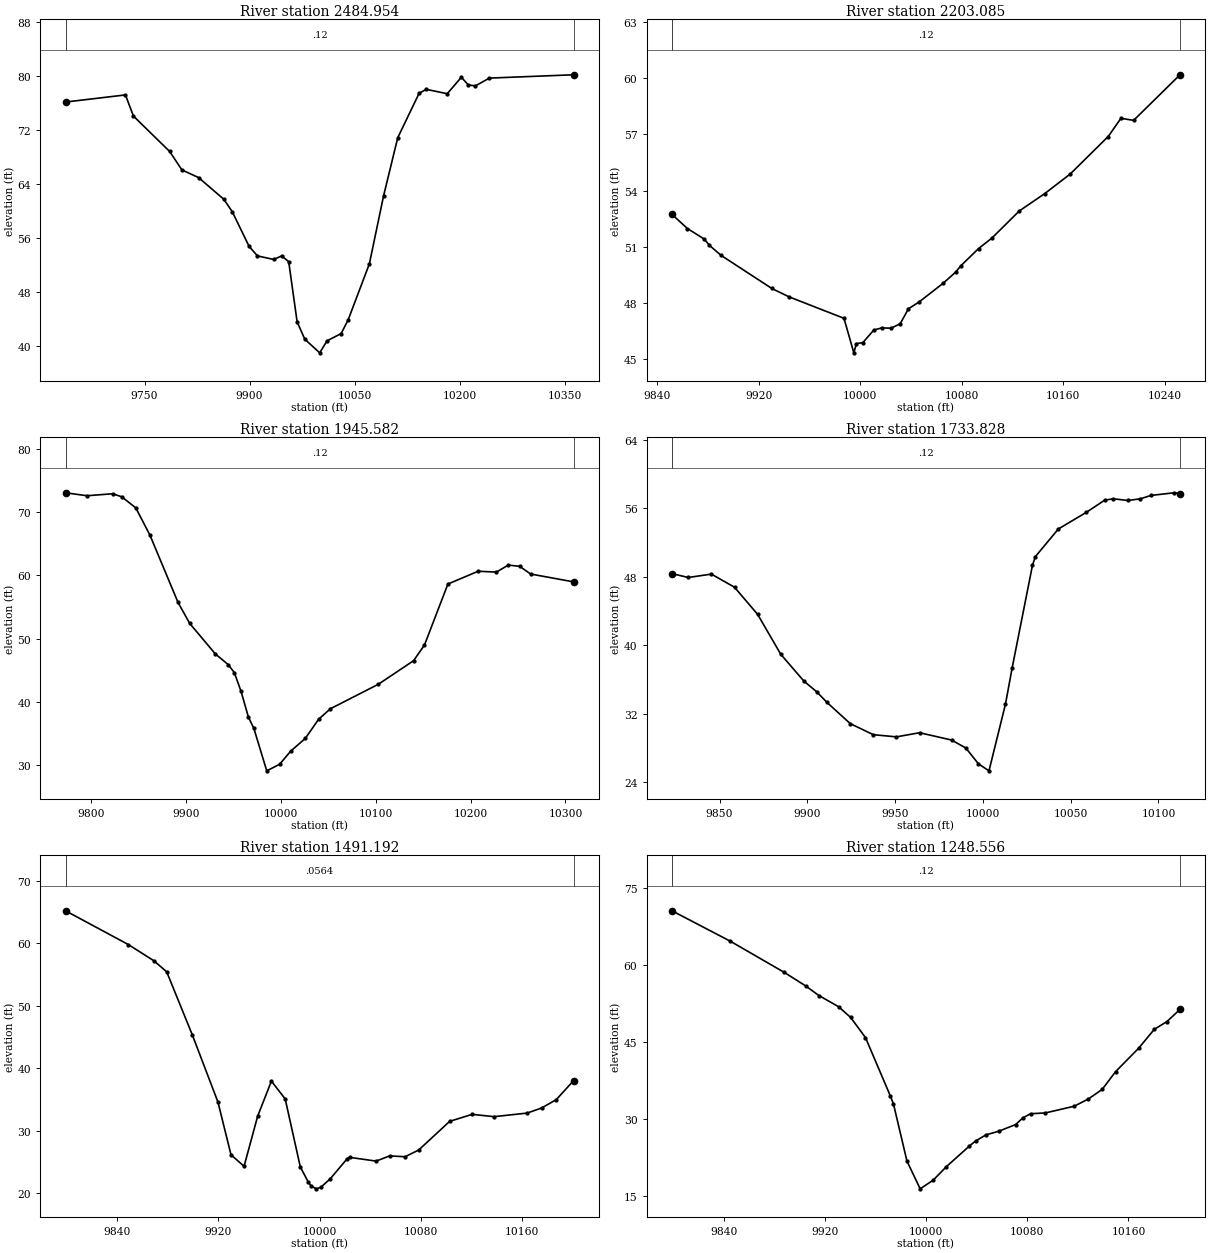
Type RM Length L Ch R = 1 ,2484.954,281.869600,281.869600,281.869600
XS GIS Cut Line= 6
 983871.89074256 753803.64568638983761.571647677753748.124624639
983610.103190351753651.591996808983543.023479989753624.589087756
983329.229591549753647.380660599983194.912944829753648.870711091
#Sta/Elev= 30
9637.07976.108519722.73277.162899734.06674.037999785.86668.792279803.43366.05718
9827.17764.930629863.31461.70882 9875.3659.866149899.45254.729369911.34653.33629
9934.59852.807199945.91653.336559955.95752.479269967.96243.583919978.96141.00316
10000.2938.9889110010.6840.7615710030.9241.8453710040.9343.8850810071.17  52.155
10091.4562.2089910111.7370.8327610142.1577.3824410152.2977.9909110182.4777.34178
10202.58  79.77810212.6478.63221 10222.778.5057510242.7479.6528210362.8880.14338
#Mann= 3 , 0 , 0
9637.079    0.12       09637.079    0.12       010362.88    0.12       0
#XS Ineff= 2 , 0
       0                               0
Bank Sta=9637.079,10362.88
Exp/Cntr=0.3,0.1

Type RM Length L Ch R = 1 ,2203.085,257.502700,257.502700,257.502700
XS GIS Cut Line= 6
 983644.49982971753534.133783117983549.881774157753426.494894236
983503.006774157753376.147671998983471.756774157 753344.02961646
983412.728996396753341.425449789 983328.52760753 753336.21711646
#Sta/Elev= 29
  9851.652.723669863.76151.968539877.07551.402959881.13551.067229890.38950.52971
9930.33248.764199943.64648.324019987.16147.170859994.91345.326099996.95645.81609
10002.0845.8758110010.6246.5417810016.7546.6567510024.2846.6452710031.4346.87776
10037.9547.68128 10046.148.03082 10065.349.0437810075.1949.6407310079.2649.97948
10093.21 50.897910103.8651.4673710125.29 52.906510145.3153.8322910165.3354.87511
10195.3856.88537 10205.457.8555510215.4257.7490510251.9660.18341
#Mann= 3 , 0 , 0
  9851.6    0.12       0  9851.6    0.12       010251.96    0.12       0
#XS Ineff= 2 , 0
       0                               0
Bank Sta=9851.6,10251.96
Exp/Cntr=0.3,0.1

Type RM Length L Ch R = 1 ,1945.582,211.753600,211.753600,211.753600
XS GIS Cut Line= 6
983884.951218635753681.703227565983701.791496426753481.182394236
 983656.65260753753422.154616445983616.577227503753361.723487839
983587.146651298753328.232583508983554.235041559753263.879207447
#Sta/Elev= 30
9772.971 73.06559795.57572.59848 9822.6472.909299832.26772.430359847.109 70.6689
9861.95266.373869891.63655.707259903.83552.411619930.90147.571699944.45745.88125
9950.96144.614149958.01641.655749965.76837.592029971.57635.770419985.13629.06849
9998.69630.1027510010.1932.1546610025.8234.20539 10039.837.2298810052.3338.89919
10102.6942.7568910139.9446.4955910151.4448.9812210176.1358.6262210208.0660.65158
 10227.260.5146110239.8761.63051 10251.961.4191810263.3160.2126910308.5958.96965
#Mann= 3 , 0 , 0
9772.971    0.12       09772.971    0.12       010308.59    0.12       0
#XS Ineff= 2 , 0
       0                               0
Bank Sta=9772.971,10308.59
Exp/Cntr=0.3,0.1

Type RM Length L Ch R = 1 ,1733.828,242.636100,242.636100,242.636100
XS GIS Cut Line= 2
983812.034551978753438.647671998983592.416496426 753250.27961646
#Sta/Elev= 30
 9822.9348.372199832.19847.922849845.37248.317169858.54646.781739871.72143.60741
9884.89538.94177 9898.0735.801849905.33334.561359911.24433.306479924.41930.84033
9937.59329.539289950.76829.284589963.94229.770029982.13328.913129990.29127.97881
9997.49426.1257910003.4725.3117210012.8533.1023510016.6437.3262710028.2149.32423
10029.8150.3446610042.9953.5989610058.9355.5401410069.3456.9612910074.2957.12542
10082.5156.9288710089.6557.1210910095.6957.5155710108.8657.8282310112.2657.74341
#Mann= 3 , 0 , 0
 9822.93    0.12       0 9822.93    0.12       010112.26    0.12       0
#XS Ineff= 2 , 0
       0                               0
Bank Sta=9822.93,10112.26
Exp/Cntr=0.3,0.1

Type RM Length L Ch R = 1 ,1491.192,242.636200,242.636200,242.636200
XS GIS Cut Line= 6
984034.442757382753219.921952673983891.803481352753241.774559453
983863.274513716753254.103933241983814.858288919753287.145501782
983779.643435379753272.697715304983672.483784191753202.968397022
#Sta/Elev= 30
9799.10465.192869848.89359.781129869.03457.195079879.104   55.449899.32445.37827
 9919.6434.620289929.95326.191439940.28524.347049950.99932.335969961.89337.96611
9972.78735.126169984.75324.252419991.06621.815929993.38621.181549997.44520.74455
   1000121.0001110008.4422.3514110021.7725.5494910023.8425.7762110044.6625.17788
10055.46 26.013910067.5325.8728310078.33 26.945310102.8331.5295410120.6232.65166
10137.9332.2821710164.0732.8522510175.6433.6755210187.1735.00981 10200.838.03667
#Mann= 3 , 0 , 0
9799.104  0.0564       09799.104  0.0564       0 10200.8  0.0564       0
#XS Ineff= 2 , 0
       09960.192                       0
Bank Sta=9799.104,10200.8
Exp/Cntr=0.3,0.1

Type RM Length L Ch R = 1 ,1248.556,242.636100,242.636100,242.636100
XS GIS Cut Line= 6
983911.496999431752938.122464666983853.707944116752984.668652919
983815.999007455753025.596631828983770.065903745753126.706957905
983683.778783262753175.670575792983624.645836727753184.518837816
#Sta/Elev= 30
9799.06470.535669845.34464.588559887.90558.530449904.75955.907119915.249 54.0279
9930.79851.854929940.34949.76198 9952.09 45.83979971.77834.448869974.22532.90081
9984.87821.79262 9995.3216.3788410005.6618.0771510015.9920.6810910034.2524.71639
10039.12 25.6914 10047.4 26.896710057.3227.5834710070.8728.9018210076.45 30.1854
 10082.631.0056210094.3331.1621610117.1832.47338 10128.333.8785110139.2535.74006
10149.8339.1964110168.1643.7820110180.4147.4309110190.4348.9523410200.8151.32799
#Mann= 3 , 0 , 0
9799.064    0.12       09799.064    0.12       010200.81    0.12       0
#XS Ineff= 2 , 0
       0                               0
Bank Sta=9799.064,10200.81
Exp/Cntr=0.3,0.1

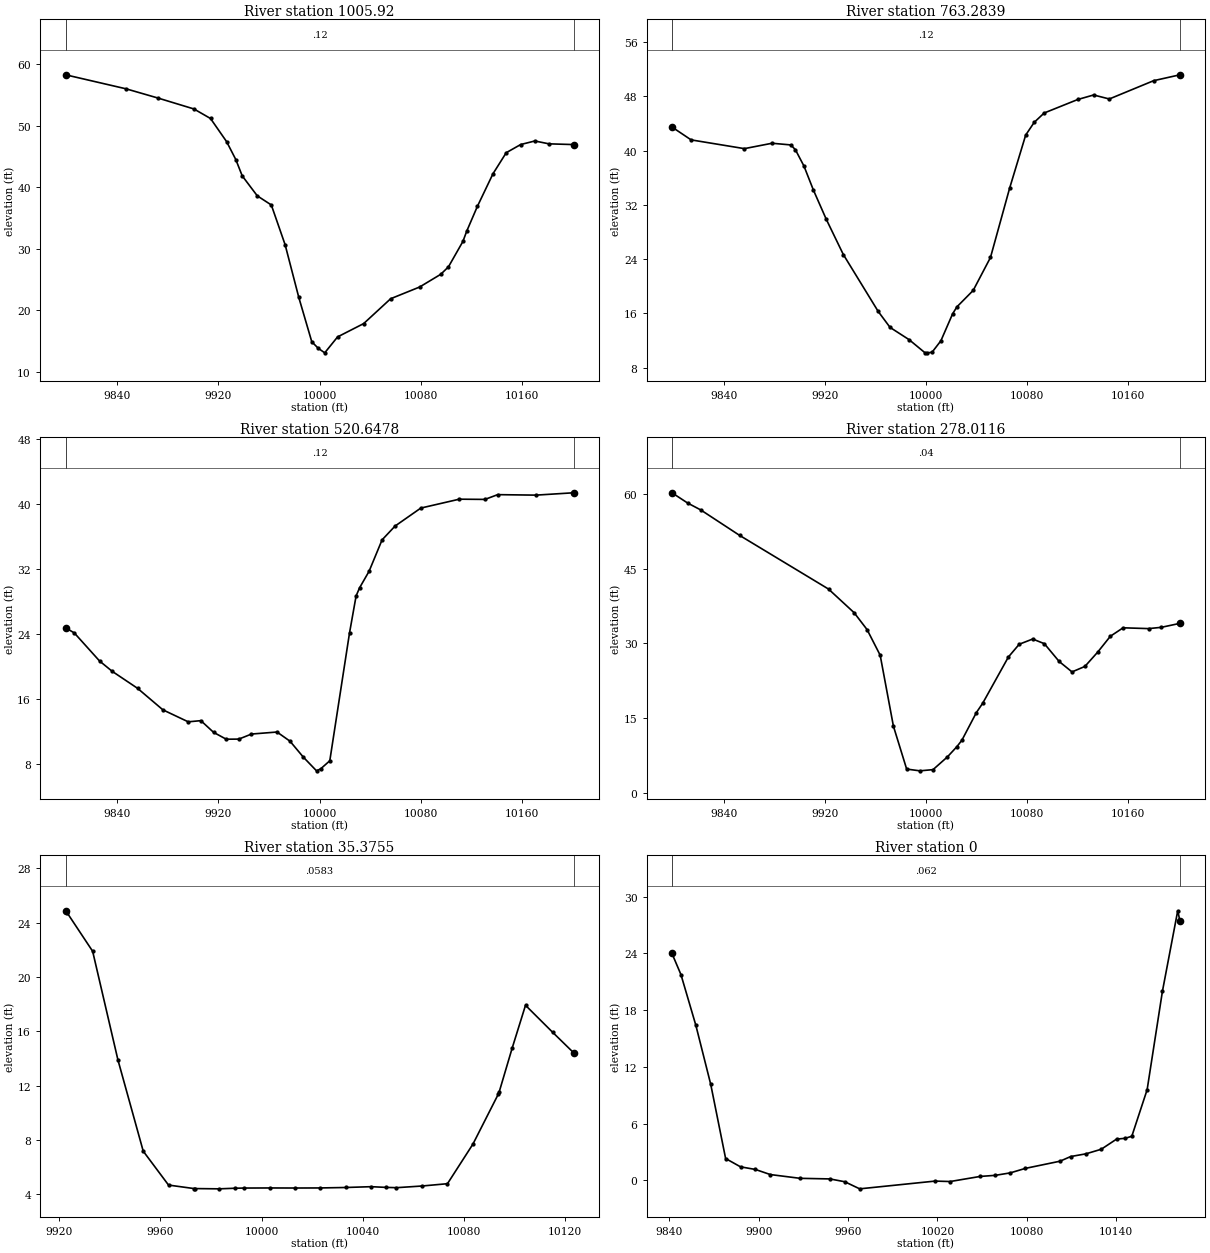
Type RM Length L Ch R = 1 , 1005.92,242.636100,242.636100,242.636100
XS GIS Cut Line= 6
983820.633055563 752856.21454382983739.495007114752928.949162965
 983703.15039631752955.266842103983676.453529767752966.941782458
983606.198321269752985.194828935983477.660127767753054.426730499
#Sta/Elev= 30
9799.09158.279159846.94655.999749872.17954.503639900.66552.725549913.77851.17779
9926.50447.419099933.77344.509119938.87641.852689950.77738.610729961.87437.12752
9972.78930.67269 9983.61 22.1068 9993.8814.90217    999913.8467710004.1113.10757
10014.2815.69562 10034.917.8580510056.2621.8982910079.1223.7961910095.8425.86142
10101.9727.0780410113.3931.1994910116.5132.9169410124.8236.8850410137.1842.19514
10147.6745.6199810159.08 46.945610170.2847.5237110181.4947.0597310200.9146.94165
#Mann= 3 , 0 , 0
9799.091    0.12       09799.091    0.12       010200.91    0.12       0
#XS Ineff= 2 , 0
       0                               0
Bank Sta=9799.091,10200.91
Exp/Cntr=0.3,0.1

Type RM Length L Ch R = 1 ,763.2839,242.636100,242.636100,242.636100
XS GIS Cut Line= 6
983600.951227655752716.250465569983562.888298207752743.225354816
983520.023135564752781.901651925983401.458618402752919.859044655
 983351.45898907752959.424737637983307.019575771752985.467047732
#Sta/Elev= 30
 9799.0843.472379814.21241.579449856.35740.289479878.23741.083039893.16440.83412
9896.76340.108889903.46737.727259910.95834.176269921.12129.87795  9934.624.68782
9962.16616.304959971.57213.943499986.65612.134939999.18110.21032   1000110.19679
10004.7610.27511 10011.811.9806410021.05 15.944610024.4716.9760110037.34 19.3997
   1005124.2518910066.1334.4535810078.8442.28369 10085.6 44.167710093.4645.53935
10120.1347.5362310132.5748.19525   1014547.6074510180.0750.3038810200.91 51.1734
#Mann= 3 , 0 , 0
 9799.08    0.12       0 9799.08    0.12       010200.91    0.12       0
#XS Ineff= 2 , 0
       0                               0
Bank Sta=9799.08,10200.91
Exp/Cntr=0.3,0.1

Type RM Length L Ch R = 1 ,520.6478,242.636200,242.636200,242.636200
XS GIS Cut Line= 6
983491.948886146 752680.06731382983371.117123998752673.878899703
983336.758225563752674.738827005983317.675793326752678.221395631
 983227.74011002752703.098302858 983095.49804929752722.968871215
#Sta/Elev= 30
9799.06324.746859806.01424.108829826.01820.647689836.02219.375129856.06317.28394
9876.10314.631659896.14413.155129906.16413.299629916.18411.860759926.19411.01349
9936.19711.02655  9946.211.649229966.39711.897999976.65210.769669987.1528.815346
9997.652 7.11554   100017.37077810008.148.35613710023.7424.0983910028.9628.66949
10031.6929.6623110039.2331.70795 10049.535.5729910059.7737.2752710080.1539.49317
 10110.640.5885510130.8840.5605410140.9741.1474110171.2241.0875210200.9841.37756
#Mann= 3 , 0 , 0
9799.063    0.12       09799.063    0.12       010200.98    0.12       0
#XS Ineff= 2 , 0
       0                               0
Bank Sta=9799.063,10200.98
Exp/Cntr=0.3,0.1

Type RM Length L Ch R = 1 ,278.0116,242.636100,242.636100,242.636100
XS GIS Cut Line= 6
 983667.09670995752550.154283196983598.196431211752564.615441494
983535.347441583752563.139028576983463.604567569 752543.54695764
983383.672736878752504.003978072983280.305176105752489.619187746
#Sta/Elev= 30
9799.09160.232219811.55958.158699821.86756.78312 9852.5951.672179922.88340.89265
9943.15836.138829953.38532.748639963.75227.597689974.22113.343719984.689  4.7283
9995.157 4.3744110005.564.617224 10016.97.16954810024.429.23266410028.3710.52324
10039.8516.0878410044.7917.9377410065.1527.2420710073.7129.8057710084.3730.85346
10093.5829.9171410105.2826.3478910115.4624.2465610125.6525.3485310135.7428.21463
 10145.831.4137210155.8733.1082710176.0132.9470110186.0833.2028210200.8734.00538
#Mann= 3 , 0 , 0
9799.091    0.04       09799.091    0.04       010200.87    0.04       0
#XS Ineff= 2 , 0
       0                               0
Bank Sta=9799.091,10200.87
Exp/Cntr=0.3,0.1

Type RM Length L Ch R = 1 , 35.3755,35.375500,35.375500,35.375500
XS GIS Cut Line= 5
983425.726181149752364.262669936983374.344346136752364.262669936
983299.043381035752367.806244761983254.748695701752373.121606976
983227.285990834 752383.75233148
#Sta/Elev= 27
9922.45624.876849923.18224.705519933.18221.896619943.18213.894479953.182 7.17693
9963.1824.6820719973.1824.4268369973.8384.4237089983.1934.4044839989.5244.449351
9993.2044.46257310003.214.46932610013.23 4.4646210023.244.47068410033.254.503942
10043.264.56324410049.224.51081310053.294.48958110063.374.61279810073.444.782684
10083.517.69801610093.5811.3920510093.8311.5045510099.0414.7787610104.2917.91811
10115.0115.9322210123.2814.42815
#Mann= 3 , 0 , 0
9922.456  0.0583       09922.456  0.0583       010123.28  0.0583       0
#XS Ineff= 2 , 0
       0                               0
Bank Sta=9922.456,10123.28
Exp/Cntr=0.3,0.1

Type RM Length L Ch R = 1 ,       0,0.000000,0.000000,0.000000
XS GIS Cut Line= 6
 983501.02714625752324.397453114 983404.46473217752324.397453114
983366.691173822 752325.85459967983346.356152058752330.012801781
983241.458327711752345.068269163983163.501643896752363.376776218
#Sta/Elev= 29
9841.76923.993889847.79621.760229857.79616.401169867.796   10.159877.7962.304235
9887.7961.4257859897.7961.1482989907.7960.6085959927.7960.2097779947.8030.146831
 9957.81-0.151619967.818-0.9021110018.46-0.0825610028.57-0.1288210048.770.410557
10058.870.52525610068.980.78675610079.081.26162810102.382.022315 10109.52.513225
10119.772.80131710130.043.28453110140.314.355507 10146.34.44765610150.584.664451
10160.869.58558210171.1319.99633 10181.428.5101910182.9427.40503
#Mann= 3 , 0 , 0
9841.769   0.062       09841.769   0.062       010182.94   0.062       0
#XS Ineff= 2 , 0
       0                               0
Bank Sta=9841.769,10182.94
Exp/Cntr=0.3,0.1